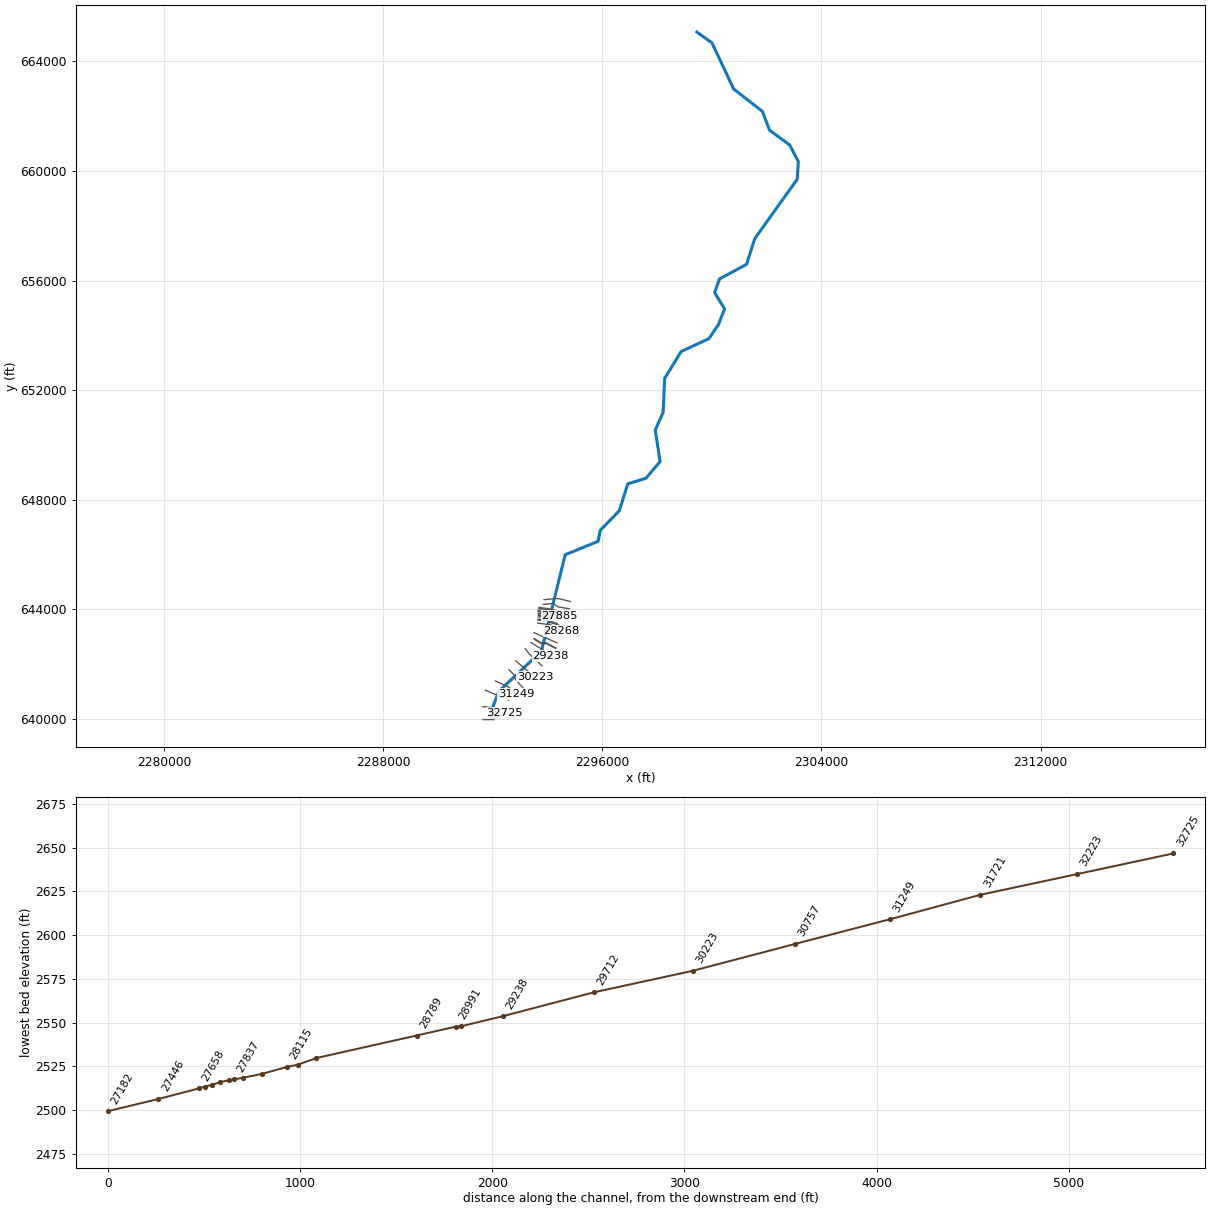
--- RFFILESCK.prj (project) ---

Proj Title=RFFILESCK
Current Plan=p01
Default Exp/Contr=0,0
English Units
Geom File=g01
Flow File=f01
Plan File=p01
BEGIN DESCRIPTION:
----------MODEL BY WOOD PLC 2022----------
AFH study
Randolph County, WV
HEC-RAS Version: RAS 6.2
Vertical Datum: NAVD88
Projection: NAD 1983 StatePlane West Virginia S FIPS 4702 (US Feet)
Terrain: 1-meter LIDAR (FEMA Region III 3DEP collected 2016-2018)
Land Use: 2019 NLCD
Hydrologic Method:
WV SIR2010-5033 regression equations
Additional Model Notes:
Shared XS with FILESCK due to name change; name change at US extent as well with RFFILSCKT1S
END DESCRIPTION:
DSS Export Rating Curves= 0
DSS Export Rating Curve Sorted= 0
DSS Export Volume Flow Curves= 0
DXF OffsetX= 0
DXF OffsetY= 0
DXF ScaleX= 0
DXF ScaleY= 0

--- RFFILESCK.p01 (plan) ---

Plan Title=Floodplain
Program Version=6.20
Short Identifier=Floodplain
Geom File=g01
Flow File=f01
Subcritical Flow
K Sum by GR= 0
Std Step Tol= 0.01
Critical Tol= 0.01
Num of Std Step Trials= 20
Max Error Tol= 0.3
Flow Tol Ratio= 0.001
Split Flow NTrial= 30
Split Flow Tol= 0.02
Split Flow Ratio= 0.02
Log Output Level= 0
Friction Slope Method= 1
Unsteady Friction Slope Method= 2
Unsteady Bridges Friction Slope Method= 1
Parabolic Critical Depth
Global Vel Dist= 0 , 0 , 0
Global Log Level= 0
CheckData=True
Encroach Param=-1 ,0,0, 0
Mapping Interval=1HOUR
Computation Time Step Use Courant=        0
Computation Time Step Use Time Series=    0
Computation Time Step Count To Double=0
Computation Time Step Max Doubling=0
Computation Time Step Max Halving=0
Computation Time Step Residence Courant=0
Run HTab= 0
Run UNet= 0
Run Sediment= 0
Run PostProcess= 0
Run WQNet= 0
Run RASMapper=-1
UNET Theta= 0
UNET Theta Warmup= 0
UNET ZTol= 0
UNET ZSATol= 0
UNET MxIter= 0
UNET Max Iter WO Improvement= 0
UNET MaxInSteps= 0
UNET DtIC= 0
UNET DtMin= 0
UNET MaxCRTS= 0
UNET WFStab= 0
UNET SFStab= 0
UNET WFX= 1
UNET SFX= 1
UNET Gravity=32.174
UNET 1D Methodology=Finite Difference
UNET DSS MLevel= 1
UNET Pardiso=0
UNET DZMax Abort= 0
UNET Use Existing IB Tables= 0
UNET Froude Reduction=False
UNET Froude Limit= 0
UNET Froude Power= 0
UNET D1 Cores= 0
UNET WindReference=Eulerian
UNET WindDragFormulation=Hsu (1988)
UNET D2 Coriolis=0
UNET D2 Cores= 0
UNET D2 Theta= 1
UNET D2 Theta Warmup= 1
UNET D2 Z Tol= 0.01
UNET D2 Volume Tol= 0.01
UNET D2 Max Iterations= 20
UNET D2 Equation= 0
UNET D2 RampUpFraction=0.1
UNET D2 TimeSlices= 1
UNET D2 Turbulence Formulation=Non-Conservative (original)
UNET D2 Eddy Viscosity=0.3
UNET D2 Transverse Eddy Viscosity=0.1
UNET D2 Smagorinsky Mixing=0
UNET D2 BCVolumeCheck=0
UNET D2 Cores=0
UNET D2 SolverType=PARDISO (Direct)
UNET D2 Minimum Iterations= 2147483647
UNET D2 Maximum Iterations= 2147483647
UNET D2 Restart Number= 10
UNET D2 Relaxation Coeff=1.3
UNET D2 SOR Precondition Iterations= 10
UNET D2 ILUT Maximum Fill= 8
UNET D2 ILUT Tolerance=1E-08
UNET D1D2 MaxIter= 0
UNET D1D2 ZTol=0.01
UNET D1D2 QTol=0.1
UNET D1D2 MinQTol=1
Write IC File= 0
Write IC File at Fixed DateTime=0
Write IC File at Sim End=0
Echo Input=False
Echo Parameters=False
Echo Output=False
Write Detailed= 0
HDF Write Warmup=0
HDF Write Time Slices=0
HDF Flush=0
HDF Compression= 1
HDF Chunk Size= 1
HDF Spatial Parts= 1
HDF Use Max Rows=0
HDF Fixed Rows= 1
Calibration Method= 0
Calibration Iterations= 20
Calibration Max Change=0.05
Calibration Tolerance=0.2
Calibration Maximum=1.5
Calibration Minimum=0.5
Calibration Optimization Method= 1
WQ AD Non Conservative
WQ ULTIMATE=-1
WQ Max Comp Step=1HOUR
WQ Output Interval=15MIN
WQ Output Selected Increments= 0
WQ Output face flow=0
WQ Output face velocity=0
WQ Output face area=0
WQ Output face dispersion=0
WQ Output cell volume=0
WQ Output cell surface area=0
WQ Output cell continuity=0
WQ Output cumulative cell continuity=0
WQ Output face conc=0
WQ Output face dconc_dx=0
WQ Output face courant=0
WQ Output face peclet=0
WQ Output face adv mass=0
WQ Output face disp mass=0
WQ Output cell mass=0
WQ Output cell source sink temp=0
WQ Output nsm pathways=0
WQ Output nsm derived pathways=0
WQ Create Restart=0
WQ Fixed Restart=0
WQ System Summary=0
WQ Write To DSS=0
Sorting and Armoring Iterations= 10
XS Update Threshold= 0.02
Bed Roughness Predictor= 0
Hydraulics Update Threshold= 0.02
Energy Slope Method= 1
Volume Change Method= 1
Sediment Retention Method= 0
Sediment TS Multiplier= 1
Warm Up Method= 0
XS Weighting Method= 0
Number of US Weighted Cross Sections= 1
Number of DS Weighted Cross Sections= 1
Upstream XS Weight=0
Main XS Weight=1
Downstream XS Weight=0
Number of DS XS's Weighted with US Boundary= 1
Upstream Boundary Weight= 1
Weight of XSs Associated with US Boundary= 0
Number of US XS's Weighted with DS Boundary= 1
Downstream Boundary Weight= 0.5
Weight of XSs Associated with DS Boundary= 0.5
Percentile Method= 0
Sediment Output Level= 3
Mass or Volume Output= 0
Output Increment Type= 1
Profile and TS Output Increment= 1
Transport Output Increment 1
XS Output Flag= 0
XS Output Increment= 10
Read HDF5 Sediment Hotstart= 0
Sediment Hotstart Type= 0
Write Gradation File= 0
Read Gradation Hotstart= 0
Write HDF5 File= 1
Write Binary Output= 1
Write DSS Sediment File= 0
DSS Sediment Output Type= 1
SV Curve= 0
Specific Gage Flag= 0
Subcell Erosion Methods= 0
Subcell Deposition Methods= 0
Advection Scheme= 1
Matrix Solver= 0
Implicit Weighting Factor= 1
Maximum Outer Loop Convergence Iterations= 5
Convergence Maximum Absolute= 0.001
Convergence RMSE= 0.0001
Grain Fractions Max Abs Error= 0.001
Max Subgrid Regions= 1
Max Subgrid Length Scale= 3.402823E+38
Initial Layer Thickness= 3.402823E+38
Min Layer Thickness= 3.402823E+38
Max Layer Thickness= 3.402823E+38
Number of Layers= 5

--- RFFILESCK.f01 (steady flow) ---

Flow Title=Flow
Program Version=6.20
Number of Profiles= 1
Profile Names=P100yr
River Rch & RM=RFFILESCK,Main            ,32725
     640
River Rch & RM=RFFILESCK,Main            ,28268
     840
River Rch & RM=RFFILESCK,Main            ,25948
     970
River Rch & RM=RFFILESCK,Main            ,21848
    1160
River Rch & RM=RFFILESCK,Main            ,21667
    1290
River Rch & RM=RFFILESCK,Main            ,13179
    1720
River Rch & RM=RFFILESCK,Main            ,5701
    2140
River Rch & RM=RFFILESCK,Main            ,0
    3380
Boundary for River Rch & Prof#=RFFILESCK,Main            , 1
Up Type= 0
Dn Type= 1
Dn Known WS=2053
DSS Import GetInterval= 0
DSS Import GetPeak= 0
DSS Import FillOption= 0

--- RFFILESCK.g01 (geometry) ---

Geom Title=Geometry
Program Version=6.20

River Reach=RFFILESCK       ,Main
Reach XY= 30
2292016.78768442640003.0166700862291876.66386046640111.812029496
2292219.96008994641005.8791389912293775.63709667642468.269914985
2294643.01790778645991.5420679152295842.81800163646481.465956807
2295922.77092575646882.3939607292296617.11894649647595.752114072
2296930.69213825648582.4489595592297592.73707399648784.193962887
2298108.12515081649394.3820469982297932.74689263650549.520156652
2298218.84212099651189.0500455652298276.13892241652431.390080571
2298876.15806355653412.2329351462299888.39390001653878.498078749
2300239.63105838654399.9376526622300462.86716047654966.510994568
 2300099.6608659655561.6859853272300276.04010631656060.472061247
2301265.21693376656595.443104148 2301561.8918653657528.620043576
2303116.15286441659702.9221254142303154.18001933660349.214139909
2302839.35912667660952.8461347222302105.79005575661487.986140564
 2301843.6980602662177.3410610712300794.78808455662993.635032162
2300002.11808202664678.6989192372299452.53093168665072.852208212

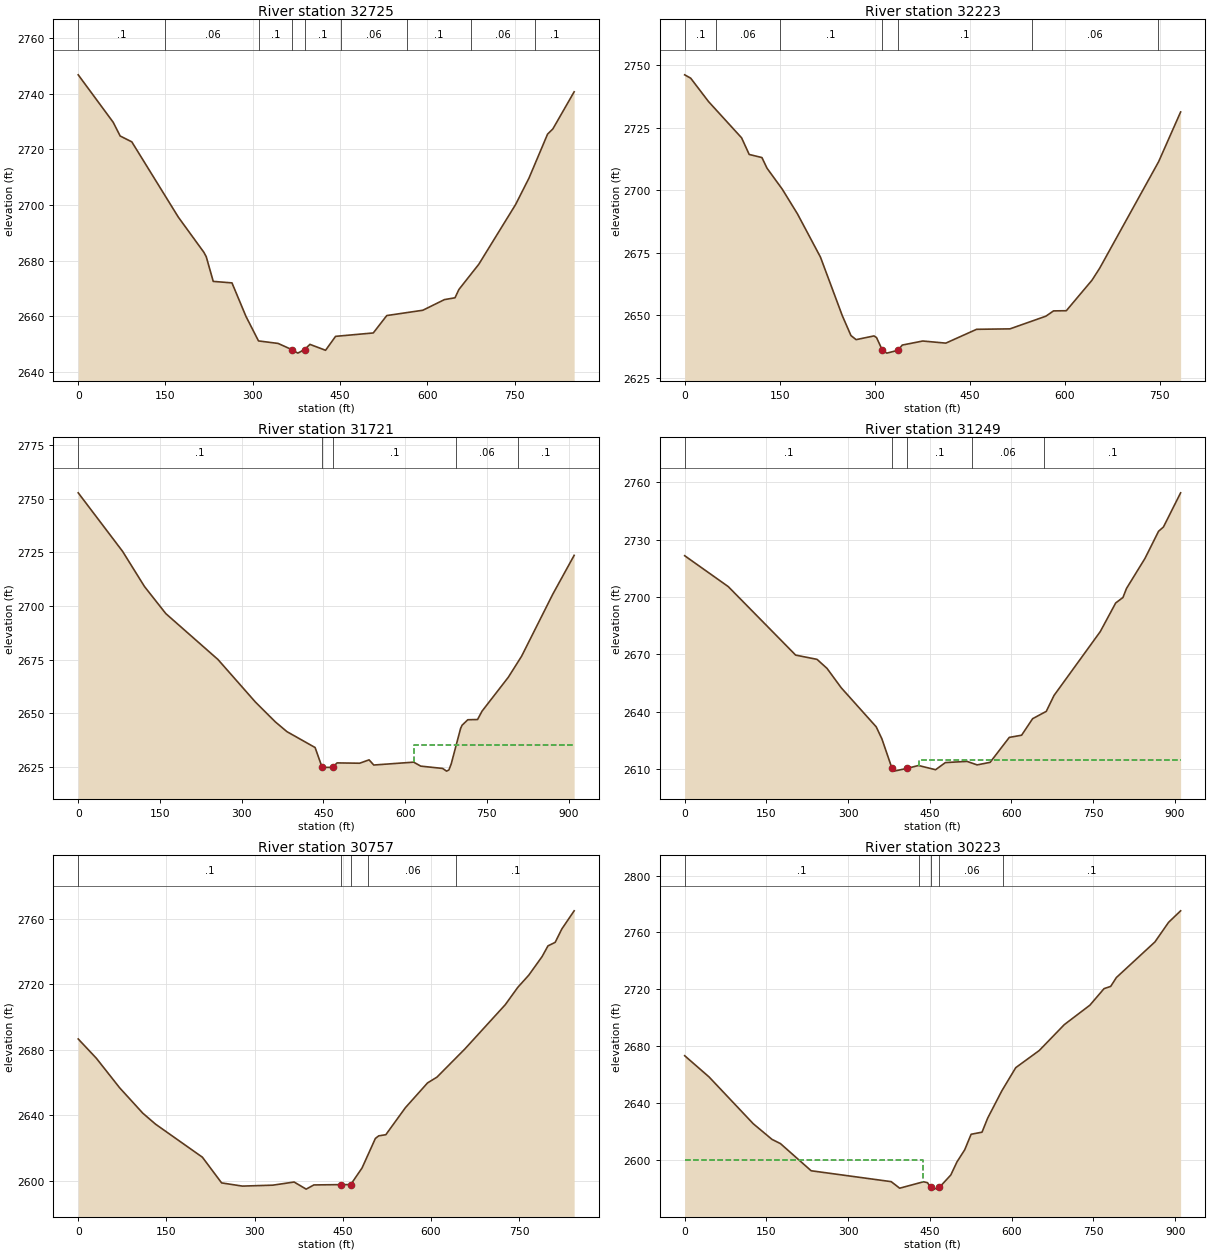
Type RM Length L Ch R = 1 ,32725   ,506.9,501.5,496.9
XS GIS Cut Line= 4
2291640.08272648639974.7499509422291941.32283109639972.744093601
2292138.83302607640052.7463024162292436.38430207640213.389838288
#Sta/Elev= 30
       0 2746.76    60.1 2729.72    72.1 2724.78    92.1 2722.68   172.1 2695.62
     216 2682.99   220.1 2681.39   232.1 2672.53   264.3 2671.99   288.4 2659.94
   309.9 2651.14   343.7 2650.23  367.382647.995   377.5 2646.75  389.042648.029
   398.3  2649.9   425.2 2647.77   442.4 2652.78   507.2    2654   530.4 2660.25
   592.4 2662.16   629.5 2665.98   647.7 2666.64   654.4 2669.62   688.6 2678.69
   751.8 2700.13     775 2709.71   806.8 2725.45   815.9 2727.32   852.5 2740.66
#Mann= 9 ,-1,0
       0      .1       0     150     .06       0  311.25      .1       0
  367.38    .045       0  389.04      .1       0  451.25     .06       0
  564.34      .1       0  674.34     .06       0  784.34      .1       0
Bank Sta=367.38,389.04
XS Rating Curve= 0 ,0
Exp/Cntr=0.3,0.1

Type RM Length L Ch R = 1 ,32223   ,506.2,502.4,500.4
XS GIS Cut Line= 4
2291634.69944633640446.0278047322291906.62880008640420.448032545
 2292128.4422632 640385.08370635     2292410.473      640340.874
#Sta/Elev= 30
       0 2746.15     9.5 2744.81    37.6 2735.48    89.9 2720.96   101.9 2714.32
     122 2713.08     130 2708.84   154.2 2700.41   178.3 2690.49   214.4 2673.31
     249 2649.83   262.6 2641.93   270.7  2640.3     299 2641.79     303 2641.12
  312.272636.039   319.2 2634.91  336.77 2636.04   343.6 2638.13     376 2639.75
   412.4 2638.91     461 2644.43   513.7 2644.61   570.4 2649.67   582.5 2651.79
   602.7 2651.86   643.2 2664.05   655.4 2668.86   748.5 2711.44   783.2  2731.3
#Mann= 7 ,-1,0
       0      .1       0      50     .06       0     150      .1       0
  312.27    .045       0  336.77      .1       0  547.74     .06       0
  747.74      .1       0
Bank Sta=312.27,336.77
XS Rating Curve= 0 ,0
Exp/Cntr=0.3,0.1

Type RM Length L Ch R = 1 ,31721   ,471.1,472.2,471.8
XS GIS Cut Line= 4
     2291732.259      641048.0922292122.50917832640881.447410839
2292384.56260728640776.419828765     2292567.368      640686.575
#Sta/Elev= 30
       0 2752.65    81.4 2725.42   121.7 2709.01   160.8 2696.42   256.5 2675.06
   325.2 2655.26   361.8 2646.02   383.1 2641.47   434.8 2634.08   447.7 2624.84
  467.082624.834   475.1 2626.92   516.6 2626.77   533.9 2628.34   542.5 2625.93
   615.7 2627.27   628.7 2625.42   668.9 2624.34   676.1 2623.09   680.4 2623.63
   684.7  2626.5   701.9 2642.99   704.6 2644.46   715.1 2647.01     733 2647.11
   741.2    2651   789.5 2666.81   813.8 2676.57   871.1 2705.47   910.3 2723.54
#Mann= 5 ,-1,0
       0      .1       0   447.7    .045       0  467.08      .1       0
  694.34     .06       0  806.66      .1       0
#XS Ineff= 2 , 0
                          616.25         2635.35
Permanent Ineff=
       F       F
Bank Sta=447.7,467.08
XS Rating Curve= 0 ,0
Exp/Cntr=0.3,0.1

Type RM Length L Ch R = 1 ,31249   ,500,492,481.1
XS GIS Cut Line= 4
2292094.91572233641386.1323883382292429.23384349641232.861645031
2292583.50175267641154.733666357  2292857.356167640905.940638834
#Sta/Elev= 30
       0 2721.56    80.1 2705.42   203.8 2669.65     243 2667.44   261.4 2662.72
   287.4 2652.62   351.7  2632.2   362.2 2625.89  380.692610.517   384.5 2609.06
   408.4  2610.5   429.4    2612   460.7 2609.79   478.7 2613.52   518.5 2614.15
     537 2612.31   560.9 2613.66   596.1 2626.68   618.7 2627.82   638.9 2636.44
     664 2640.27   678.2 2648.56   763.2 2681.95   791.5  2696.9   804.8 2699.74
   811.3 2704.46   845.3 2720.18   870.2 2734.33   879.2 2736.59   910.7 2754.41
#Mann= 5 ,-1,0
       0      .1       0  380.69    .045       0   408.4      .1       0
  527.78     .06       0   660.7      .1       0
#XS Ineff= 2 , 0
                          429.42         2614.91
Permanent Ineff=
       F       F
Bank Sta=380.69,408.4
XS Rating Curve= 0 ,0
Exp/Cntr=0.3,0.1

Type RM Length L Ch R = 1 ,30757   ,528.2,533.1,536.1
XS GIS Cut Line= 4
2292590.28055534641793.9423567182292760.95640719641624.012240899
2292857.16196177641401.4386305352293101.09617391641136.486440216
#Sta/Elev= 30
       0 2686.71    30.9 2674.91    70.4 2656.91   109.9 2641.36   131.5 2634.68
   211.2  2614.5   243.9  2598.8   279.2 2596.85   331.1 2597.42   367.2 2599.34
   387.7    2595   400.8 2597.56  446.642597.749   463.42597.751   482.8 2607.95
   505.4 2625.94   511.1 2627.53   523.2 2628.24   556.4  2644.7   594.1 2659.85
   610.2 2663.41   657.7 2680.62   726.3 2707.61   747.6 2718.21   766.4  2725.7
     789 2737.04     799 2743.56   811.2  2745.7   822.5 2753.86   843.5 2764.96
#Mann= 5 ,-1,0
       0      .1       0  446.64    .045       0   463.4      .1       0
  493.32     .06       0  643.32      .1       0
Bank Sta=446.64,463.4
XS Rating Curve= 0 ,0
Exp/Cntr=0.3,0.1

Type RM Length L Ch R = 1 ,30223   ,510.8,511,510
XS GIS Cut Line= 3
     2292837.181      642117.842     2293186.613      641826.427
     2293536.045      641535.013
#Sta/Elev= 30
       0 2673.38    44.8 2658.44   125.9 2625.54   160.2 2614.58   175.8 2611.58
   232.1 2592.51   378.9 2584.86   394.5 2580.25   438.2 2584.77   445.6 2584.13
   451.3 2580.77   456.9  2579.6  467.452580.883   488.3 2589.53   499.6 2598.72
   513.8 2607.23   525.6 2618.17   545.6 2619.63     556 2629.54     582 2648.73
   607.5    2665   650.6 2677.04   696.6 2695.24   743.5 2708.89   769.5 2720.54
   781.7 2722.11   792.1 2728.33   862.9 2753.38   887.9 2767.14     910 2775.23
#Mann= 5 ,-1,0
       0      .1       0     430     .06       0   451.3    .045       0
  467.45     .06       0     585      .1       0
#XS Ineff= 2 , 0
          437.09  2599.9
Permanent Ineff=
       F       F
Bank Sta=451.3,467.45
XS Rating Curve= 0 ,0
Exp/Cntr=0.3,0.1

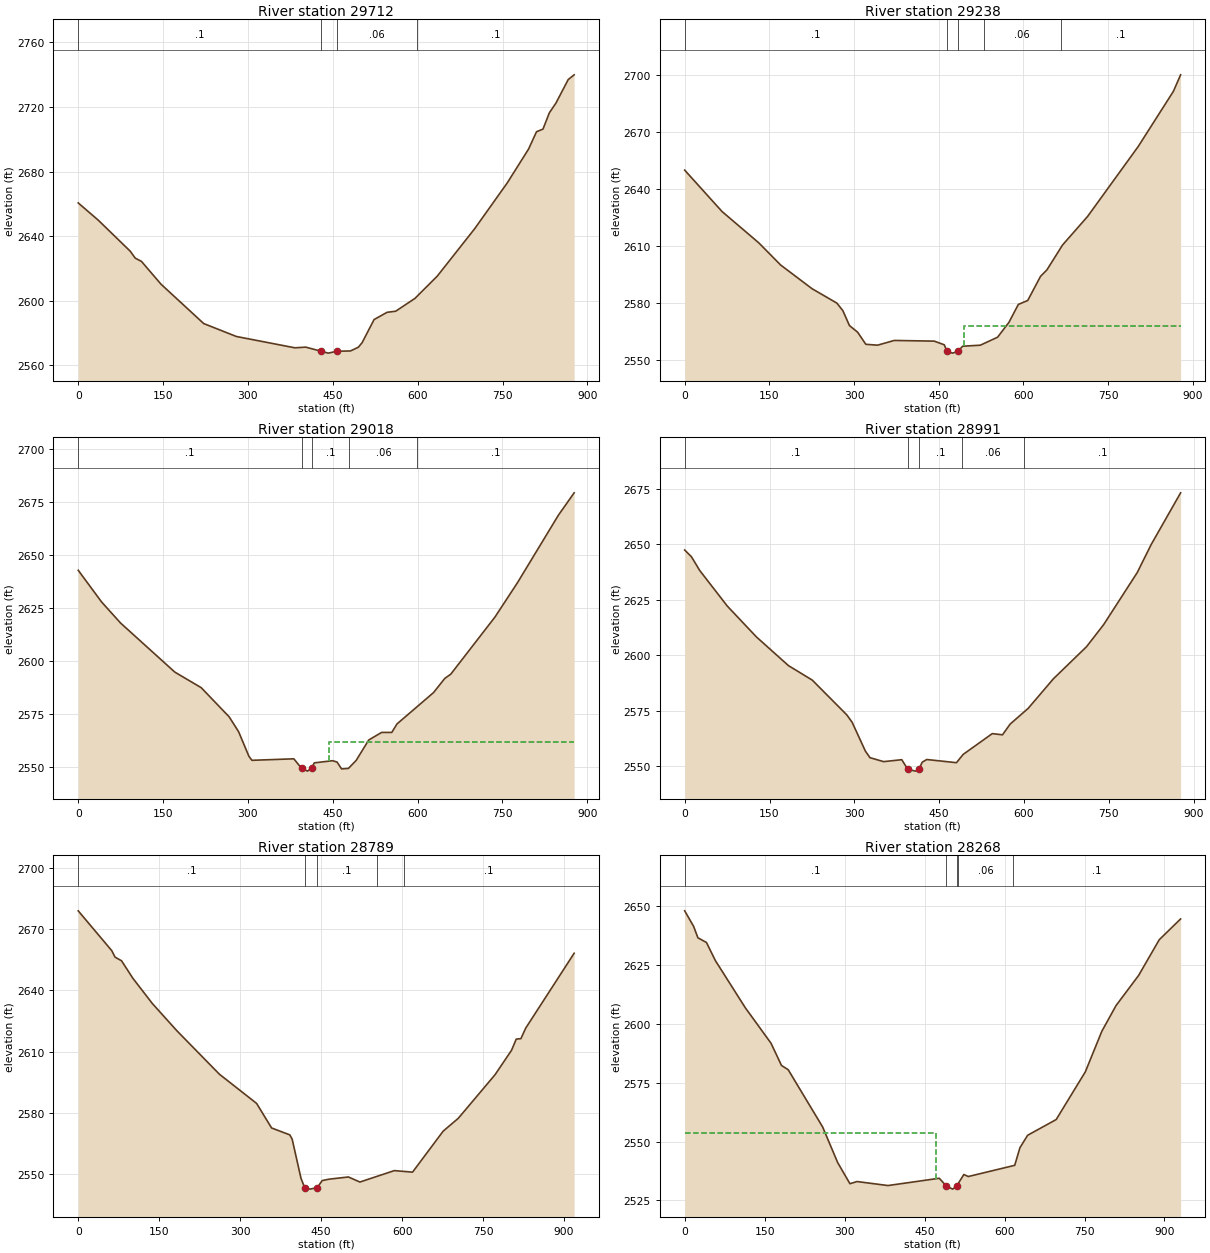
Type RM Length L Ch R = 1 ,29712   ,473.7,474.8,474.5
XS GIS Cut Line= 4
2293186.24023672 642560.17492095 2293349.5651655642350.554196842
2293545.25845101642190.1717062372293794.57434212641933.624289417
#Sta/Elev= 30
       0 2660.54    35.7 2649.74    91.9 2630.61   100.8 2626.29   111.8 2624.28
   146.3 2610.16   221.8 2585.74   279.5 2577.73   382.9 2570.71   402.2 2571.12
  429.412568.568   441.9 2567.41  457.34 2568.57   481.2 2568.76   495.1 2571.07
   501.8  2573.9   522.9 2588.22   545.9 2592.72   561.1 2593.39   595.1 2601.33
   634.7  2615.2   700.9 2644.63   758.3 2672.95   795.9 2693.88     810 2704.66
   821.4 2706.27   832.7 2716.39   844.4 2722.46     866    2737   876.5 2739.93
#Mann= 4 ,-1,0
       0      .1       0  429.41    .045       0  457.34     .06       0
  598.76      .1       0
Bank Sta=429.41,457.34
XS Rating Curve= 0 ,0
Exp/Cntr=0.3,0.1

Type RM Length L Ch R = 1 ,29238   ,214.5,219.5,224.7
XS GIS Cut Line= 4
     2293392.962      642788.3182293664.02112046642618.601556979
2293855.23905989642516.9633850952294114.72241086642293.719111282
#Sta/Elev= 30
       0 2649.97    66.2  2628.2   131.2 2611.75     170 2600.08   225.6 2587.62
   269.7 2580.02   280.3 2576.05   291.9 2568.23   306.4 2564.74     321 2558.36
   341.7  2557.9   371.3 2560.39   442.3 2560.03     460 2558.09  464.622554.737
   474.8 2553.72   484.42554.737   492.5 2557.36   523.8 2557.89   554.4 2562.09
   574.5 2569.89   591.2 2579.34   607.8  2581.4   630.5 2594.11   641.8 2597.49
   669.5 2610.59   713.9 2625.61   803.5 2662.36   865.9 2691.41   878.7 2700.09
#Mann= 5 ,-1,0
       0      .1       0  464.62    .045       0   484.4      .1       0
  529.81     .06       0  666.36      .1       0
#XS Ineff= 2 , 0
                           494.3         2567.79
Permanent Ineff=
       F       F
Bank Sta=464.62,484.4
XS Rating Curve= 0 ,0
Exp/Cntr=0.3,0.1

Type RM Length L Ch R = 1 ,29018   ,26.9,26.9,26.9
XS GIS Cut Line= 4
2293514.71559644642906.9027190512293786.73410472642739.381294488
2293946.33953953642754.9525564212294296.61021181642568.244048795
#Sta/Elev= 30
       0 2642.72    41.4 2627.73      75 2617.78   170.8 2594.65   217.5 2587.29
   266.9 2573.53   283.6 2566.51   301.8 2554.93   307.1 2553.01   381.2 2553.72
  394.982549.225   405.3 2547.91   412.6 2549.36   417.4 2551.81   449.5 2552.83
   457.6  2552.2   465.6 2548.97   477.7 2549.19   491.4 2552.96   513.6 2562.59
   536.3 2566.17   554.4 2566.17   563.5 2570.15   628.2 2584.98   648.1 2591.67
   658.7 2593.68   736.8 2620.63   776.5  2636.8   849.1 2668.76   876.8 2679.26
#Mann= 5 ,-1,0
       0      .1       0  394.98    .045       0   412.6      .1       0
  479.46     .06       0  599.83      .1       0
#XS Ineff= 2 , 0
                          443.43         2561.79
Permanent Ineff=
       F       F
Bank Sta=394.98,412.6
XS Rating Curve= 0 ,0
Exp/Cntr(USF)=0,0
Exp/Cntr=0.3,0.1

Type RM Length L Ch R = 1 ,28991   ,206.7,202.7,195.4
XS GIS Cut Line= 4
2293512.08794599642933.6171653042293784.10645427642766.095740741
2293943.71188908642781.6670026742294293.98256136642594.958495048
#Sta/Elev= 30
       0 2647.45      12 2644.39    26.5 2638.25    75.3 2622.18   126.9 2608.23
   183.5  2595.3   225.6 2588.76   286.7 2573.06   296.1 2569.73   319.5 2556.74
   327.6 2553.78   351.7 2551.99   383.8 2552.87   394.42548.552     408 2547.71
  414.052548.552     420 2551.74     428 2552.95   480.5 2551.52   492.4 2555.26
   543.8 2564.63   561.9 2564.09   575.5 2568.95   607.3 2576.02     652 2589.39
   710.5 2603.84   740.7 2613.78   800.1 2637.27   824.8 2649.94   876.8 2673.24
#Mann= 5 ,-1,0
       0      .1       0   394.4    .045       0  414.05      .1       0
  489.83     .06       0  599.83      .1       0
Bank Sta=394.4,414.05
XS Rating Curve= 0 ,0
Exp/Cntr(USF)=0,0
Exp/Cntr=0.3,0.1

Type RM Length L Ch R = 1 ,28789   ,518.8,520.6,520.3
XS GIS Cut Line= 3
2293503.11419144643150.3807253652293915.59819144642963.486725365
2294342.43019144642776.722725365
#Sta/Elev= 30
       0 2678.99    62.2 2659.47    68.2 2656.32    80.3 2654.51   101.4  2645.9
   137.3  2633.6     183 2620.18   261.6 2598.95   330.5 2584.65   358.3 2572.61
     392 2569.25   396.4 2567.13   412.7 2547.99  419.49 2543.45   429.4 2542.66
   442.9 2543.41     452 2546.85     465 2547.54   500.6 2548.62   521.9 2546.13
   585.6 2551.73   619.4 2550.98   676.2 2571.08   704.1 2577.34   772.2 2598.69
   802.8 2610.67   811.5 2616.14   820.2 2616.38     829 2621.51   918.8 2658.21
#Mann= 5 ,-1,0
       0      .1       0  419.49    .045       0   442.9      .1       0
  552.85     .06       0  602.85      .1       0
Bank Sta=419.49,442.9
XS Rating Curve= 0 ,0
Exp/Cntr=0.3,0.1

Type RM Length L Ch R = 1 ,28268   ,106.1,97.5,101.7
XS GIS Cut Line= 4
 2293643.5688221643496.1147625342294092.96427004 643437.50675826
2294229.45539732643394.0141409752294505.23653966643205.950989411
#Sta/Elev= 30
       0  2647.9    16.7 2641.35    24.8 2636.46    40.9 2634.46    57.6 2626.78
   113.8 2606.74     162  2591.7   181.6 2582.29   194.2 2580.47   258.8 2556.18
     287 2541.07     310  2532.1   323.3 2533.02   381.4 2531.32   477.6 2534.41
  490.99 2531.09   502.8  2529.8   510.1 2531.09   523.7    2536   532.1 2535.15
   619.1  2539.9   628.8 2547.33   643.3 2552.65   696.9 2559.33   751.6 2579.59
   782.5 2596.78   809.1 2607.67   851.5 2620.48   890.2 2635.63   930.3 2644.47
#Mann= 5 ,-1,0
       0      .1       0  490.99    .045       0   510.1      .1       0
   513.2     .06       0  616.45      .1       0
#XS Ineff= 2 , 0
          472.12 2553.44
Permanent Ineff=
       F       F
Bank Sta=490.99,510.1
XS Rating Curve= 0 ,0
Exp/Cntr=0.3,0.1

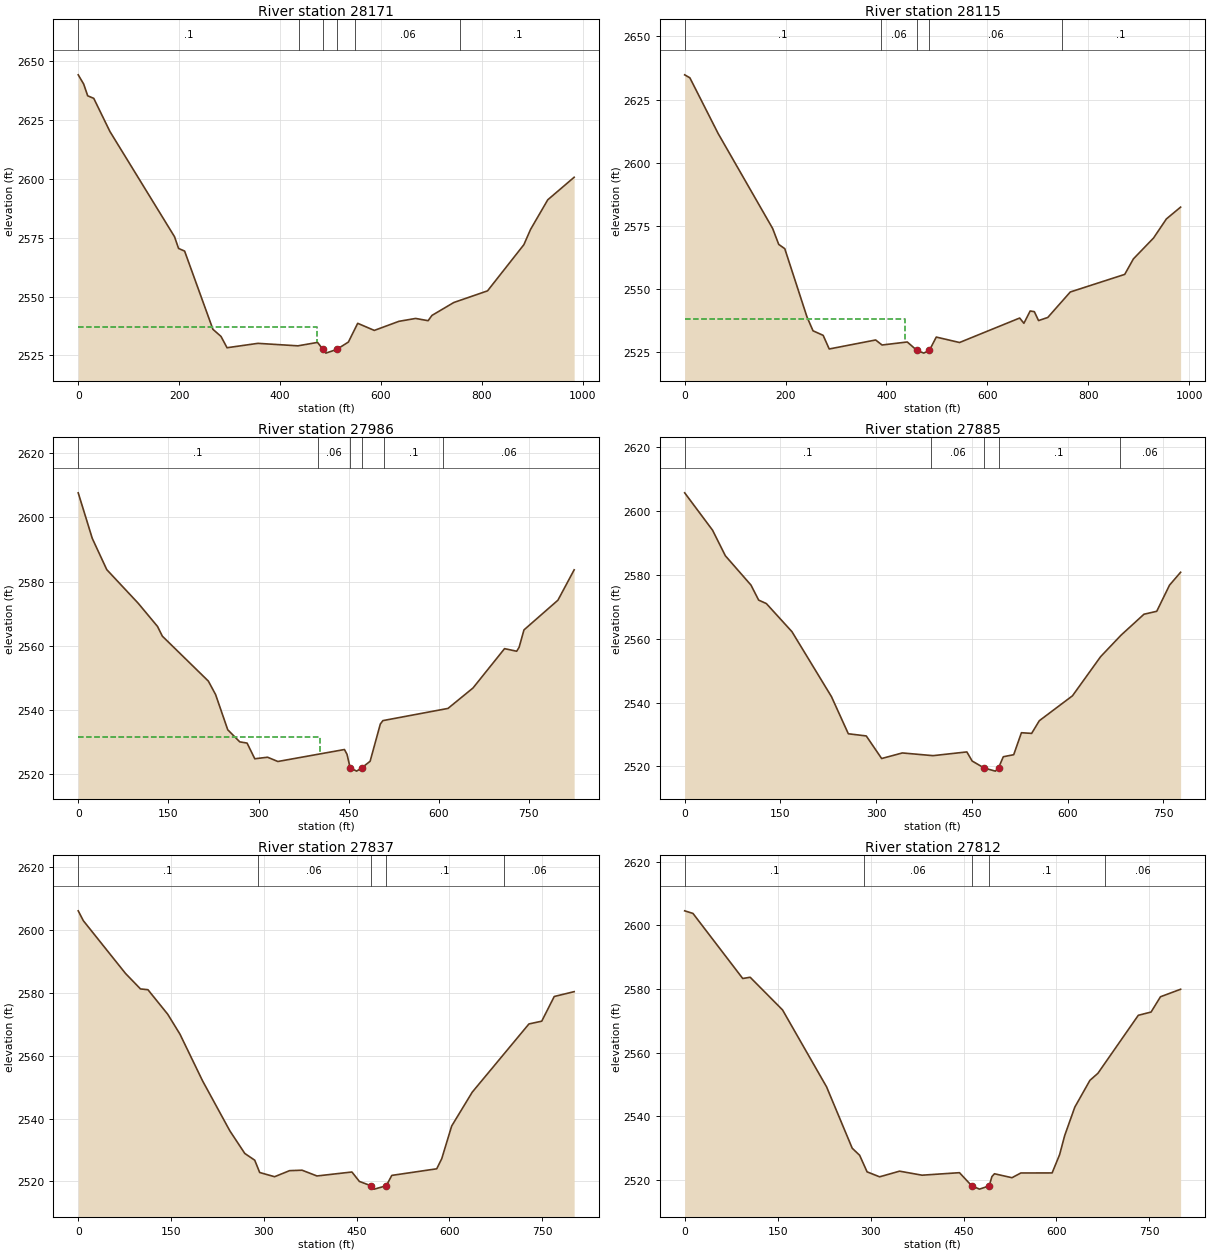
Type RM Length L Ch R = 1 ,28171   ,47.7,55.5,48.7
XS GIS Cut Line= 6
2293645.35449453643599.6227688792294036.32738976643586.803985429
2294043.04892788643550.8979222532294070.74501135643527.158422136
2294311.29952308643456.1259909662294517.60207877643289.074771371
#Sta/Elev= 30
       0  2644.3    10.8 2640.39    18.8 2635.38    30.8  2634.3    62.9 2620.19
   190.9 2575.46   198.9 2570.48   210.9 2569.35     267 2536.09     283 2533.07
     295 2528.25   356.2 2530.12   435.5 2529.06   474.4 2530.52  485.11 2527.53
   490.9 2525.96  512.312527.528   535.5 2530.66     554 2538.64   586.9 2535.62
   635.5 2539.47   668.7 2540.71   693.6 2539.75   701.1 2541.99   744.4 2547.48
   811.3 2552.44   883.4 2572.09   896.6 2578.57   930.7 2591.16     983 2600.74
#Mann= 6 ,-1,0
       0      .1       0  437.83     .06       0  485.11    .045       0
  512.31      .1       0  548.69     .06       0  757.57      .1       0
#XS Ineff= 2 , 0
          473.43 2537.04
Permanent Ineff=
       F       F
Bank Sta=485.11,512.31
XS Rating Curve= 0 ,0
Exp/Cntr(USF)=0,0
Exp/Cntr=0.3,0.1

Type RM Length L Ch R = 1 ,28115   ,126.2,128.9,128.8
XS GIS Cut Line= 6
2293657.86610076 643637.988941152294048.83899599  643625.1701577
2294055.56053412643589.2640945252294083.25661759643565.524594407
2294323.81112932643494.492163237  2294530.113685643327.440943642
#Sta/Elev= 30
       0  2634.8    10.3 2633.62    66.3  2611.6   174.4 2574.02   186.4 2567.73
   198.4 2566.04   242.4 2539.06   254.4 2533.56   274.5 2531.76   286.5 2526.37
   378.5 2529.93   391.2 2527.94   441.2 2529.14  459.872525.896   473.9 2524.73
  485.232525.897   498.7 2531.08   544.8 2528.93     664 2538.61   672.4 2536.53
   684.8  2541.4   693.1 2541.12   701.4  2537.6   719.7 2538.83   764.3 2548.91
   872.2 2555.87   889.4    2562   929.4 2570.27   954.8 2577.81     983 2582.48
#Mann= 5 ,-1,0
       0      .1       0     390     .06       0  459.87    .045       0
  485.23     .06       0  747.57      .1       0
#XS Ineff= 2 , 0
          436.04 2538.31
Permanent Ineff=
       F       F
Bank Sta=459.87,485.23
XS Rating Curve= 0 ,0
Exp/Cntr(USF)=0,0
Exp/Cntr=0.3,0.1

Type RM Length L Ch R = 1 ,27986   ,99.7,101.5,103.3
XS GIS Cut Line= 4
2293656.93890295643718.3218906312293933.63437427643748.208857917
2294158.26867677643665.2966260932294462.92292394643706.752742005
#Sta/Elev= 30
       0  2607.7    23.4 2593.47    47.5 2583.71    99.9 2573.19     132 2565.95
     140 2562.93   216.5  2548.9   228.6 2544.69   248.8 2533.69   268.8 2529.91
     281 2529.53   293.8 2524.63   315.1 2525.11   332.2 2523.78     443 2527.52
   447.3 2526.01   452.52521.809   463.3 2520.77  472.05 2521.83   485.7 2523.85
   502.7 2535.48     507 2536.55   615.3 2540.36   656.9 2546.74   709.4 2559.03
   729.6 2558.22   733.6 2559.44   741.7 2564.88   798.2 2574.16   825.2 2583.65
#Mann= 6 ,-1,0
       0      .1       0   398.3     .06       0   452.5    .045       0
  472.05     .06       0   508.3      .1       0  607.75     .06       0
#XS Ineff= 2 , 0
          401.49 2531.31
Permanent Ineff=
       F       F
Bank Sta=452.5,472.05
XS Rating Curve= 0 ,0
Exp/Cntr(USF)=0,0
Exp/Cntr=0.3,0.1

Type RM Length L Ch R = 1 ,27885   ,46.6,47.5,48.1
XS GIS Cut Line= 4
2293664.66280251643768.1660936672294038.82658751643799.817410828
2294182.38791892 643771.557306222294437.49782638643767.669635175
#Sta/Elev= 30
       0 2605.74    43.7 2594.02    63.7 2586.02   103.9 2576.81   115.9 2572.11
     128 2571.02   168.1  2562.2     230 2541.83   256.4  2530.2   284.5 2529.52
   308.6 2522.44     341 2524.19   389.1 2523.34   442.1 2524.51   450.4 2521.66
   469.42519.443   486.9 2518.49  491.68 2519.49   499.2    2523   515.5 2523.64
   527.6 2530.53   543.6 2530.32   555.6 2534.29   607.6 2542.11   651.6 2554.36
   683.6  2561.1   719.6 2567.68   739.6  2568.6   759.6 2576.79     777 2580.84
#Mann= 5 ,-1,0
       0      .1       0   385.5     .06       0   469.4    .045       0
  491.68      .1       0  681.82     .06       0
Bank Sta=469.4,491.68
XS Rating Curve= 0 ,0
Exp/Cntr(USF)=0,0
Exp/Cntr=0.3,0.1

Type RM Length L Ch R = 1 ,27837   ,26.3,24.9,25.3
XS GIS Cut Line= 4
2293663.86501525643822.6981033192293966.81333665643848.697399559
2294219.02181584 643817.444821172294460.07998791643782.189007786
#Sta/Elev= 30
       0 2606.12     8.3 2602.98    76.5 2586.18   100.7 2581.26   112.7 2581.02
   144.8 2573.19   164.5 2566.87     201 2552.03   245.2 2536.09   269.3 2528.91
   285.4 2526.75   293.4 2522.84   317.5  2521.5   341.7 2523.43   361.9 2523.57
     386 2521.74   442.5    2523   454.6    2520   473.32518.618   478.7 2517.55
     4982518.618     507 2521.92   579.6 2524.02   587.7 2527.22   603.8 2537.64
     637  2548.4   728.7 2570.12   749.4    2571   769.6 2578.85   801.8  2580.4
#Mann= 5 ,-1,0
       0      .1       0     290     .06       0   473.3    .045       0
     498      .1       0   688.2     .06       0
Bank Sta=473.3,498
XS Rating Curve= 0 ,0
Exp/Cntr(USF)=0,0
Exp/Cntr=0.3,0.1

Type RM Length L Ch R = 1 ,27812   ,43.2,44.2,42.3
XS GIS Cut Line= 4
2293666.81358515643846.8305157742293969.76190655643872.829812014
2294221.97038574643841.5772336252294460.13627066643797.644558771
#Sta/Elev= 30
       0 2604.57    13.4 2603.75    93.7 2583.29   105.7 2583.68   157.9 2573.42
     229 2549.22   270.4 2529.92   282.4  2527.7   294.4 2522.49   314.6 2520.93
   346.8 2522.71   383.1 2521.44   443.5 2522.23  463.27  2518.1   475.8 2517.06
   491.3 2518.07   495.9 2521.01     500 2521.89   528.2 2520.65   542.6 2522.14
     593 2522.15   605.1  2527.9   613.3  2533.9   629.6 2542.83     654 2551.26
   666.9 2553.48   732.1 2571.72   752.7 2572.74   767.9 2577.55   800.4 2579.91
#Mann= 5 ,-1,0
       0      .1       0     290     .06       0  463.27    .045       0
   491.3      .1       0   678.2     .06       0
Bank Sta=463.27,491.3
XS Rating Curve= 0 ,0
Exp/Cntr(USF)=0,0
Exp/Cntr=0.3,0.1

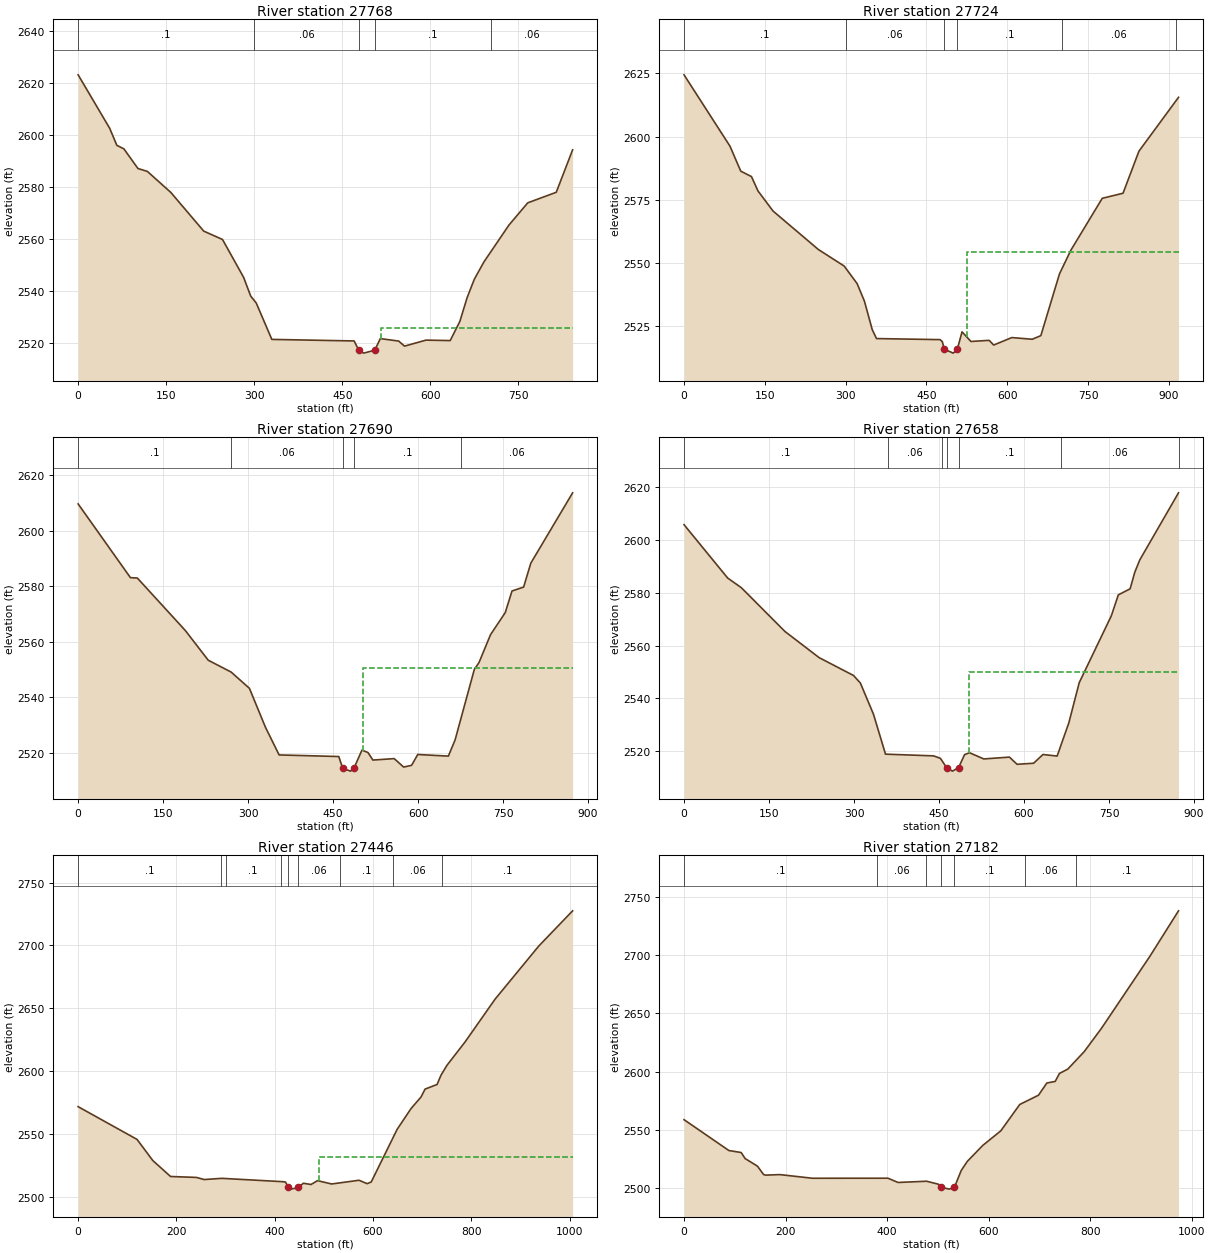
Type RM Length L Ch R = 1 ,27768   ,44.1,44,43.5
XS GIS Cut Line= 4
2293646.33385005643910.1769386882294110.06389083643898.607790062
2294167.90963396643888.9668328732294479.31255116643816.659653957
#Sta/Elev= 30
       0 2623.07    53.9 2602.44    65.9 2595.95    77.9 2594.61   101.9 2587.03
   117.9 2585.93   157.9 2577.83   213.9 2562.96   245.9 2559.74   281.9 2545.15
   293.9 2537.98   303.4 2535.28   329.9 2521.31   470.1 2520.71  477.92 2517.19
   486.3 2516.03   505.2 2517.16   514.7 2521.62   545.9 2520.67   555.9 2518.72
   592.5 2521.03   633.7 2520.86   650.1  2528.2   662.5 2537.36   674.7 2544.42
   691.2 2551.13   733.8  2565.3   765.8 2573.84   814.3 2577.89   842.2 2594.22
#Mann= 5 ,-1,0
       0      .1       0     300     .06       0  477.92    .045       0
   505.2      .1       0  702.52     .06       0
#XS Ineff= 2 , 0
                          515.57         2525.83
Permanent Ineff=
       F       F
Bank Sta=477.92,505.2
XS Rating Curve= 0 ,0
Exp/Cntr(USF)=0,0
Exp/Cntr=0.3,0.1

Type RM Length L Ch R = 1 ,27724   ,35.7,34.4,32
XS GIS Cut Line= 4
2293650.86260276643966.4250802282294013.06911622643962.440205304
2294170.50574664643932.1062604432294545.98831727643808.149551342
#Sta/Elev= 30
       0 2624.36    85.3 2596.18   105.3 2586.32   125.2 2584.17   137.3  2578.5
   165.3 2570.55   249.3 2555.39   297.3 2548.84   321.3 2541.92   334.9 2534.97
   349.3 2523.79   357.3  2520.2   475.4 2519.78   479.5 2518.97   483.22516.001
   499.8 2514.45   507.2 2515.89   516.1 2522.85   532.7 2519.05   566.4  2519.5
   574.9 2517.65   608.5 2520.59   646.5 2519.93   662.4 2521.36     697 2545.74
   718.1 2555.08   776.4 2575.59     815  2577.6   844.5 2594.19     918 2615.48
#Mann= 6 ,-1,0
       0      .1       0     300     .06       0   483.2    .045       0
   507.2      .1       0  702.56     .06       0  912.56      .1       0
#XS Ineff= 2 , 0
                          525.63         2554.26
Permanent Ineff=
       F       F
Bank Sta=483.2,507.2
XS Rating Curve= 0 ,0
Exp/Cntr=0.3,0.1

Type RM Length L Ch R = 1 ,27690   ,31.9,31.8,31.9
XS GIS Cut Line= 6
2293680.66483251   644039.330486 2294112.1108126643980.762237458
2294132.69407447643977.2587035232294158.53263724643967.623985202
2294197.07151052643951.8580824952294531.19195113643857.299715376
#Sta/Elev= 30
       0  2609.6    92.3 2583.08   104.5 2582.94   189.2 2564.07   229.6 2553.39
     270 2549.13   302.3 2543.28   330.5 2529.32   354.7 2519.32     460 2518.75
   466.9 2514.54   480.8  2513.5  486.722514.538   500.9 2521.06   511.5 2520.19
   520.2 2517.48   557.8    2518   574.5 2514.96   588.5 2515.59   599.4 2519.48
   653.4  2518.9   665.3 2524.73   699.2 2550.06   707.5 2552.56   727.8 2562.57
   753.8 2570.52   765.7 2578.28   786.2 2579.69   798.9 2588.29   872.7 2613.59
#Mann= 5 ,-1,0
       0      .1       0     270     .06       0   466.9    .045       0
  486.72      .1       0   675.5     .06       0
#XS Ineff= 2 , 0
                          503.25         2550.59
Permanent Ineff=
       F       F
Bank Sta=466.9,486.72
XS Rating Curve= 0 ,0
Exp/Cntr(USF)=0,0
Exp/Cntr=0.3,0.1

Type RM Length L Ch R = 1 ,27658   ,213.7,211.6,206.8
XS GIS Cut Line= 6
2293691.83891605644069.0216222732294123.28489615 644010.45337373
2294143.86815801644006.9498397952294169.70672078643997.315121475
2294208.24559407643981.5492187682294542.36603467643886.990851649
#Sta/Elev= 30
       0 2605.84      77 2585.63   101.3 2581.94     178  2565.4   238.5 2555.46
   299.1 2548.71   311.2 2545.86   334.3 2534.06   355.6  2518.9   440.4 2518.25
   452.5 2517.31  463.572513.766   473.7 2512.47  484.422513.763   495.1  2518.7
   503.8 2519.45     529 2517.09   574.3 2517.78   587.8 2515.06   616.9 2515.45
   633.5 2518.77   658.5 2518.17   679.2  2530.8   697.5 2545.99   754.1 2571.29
   766.5 2579.25   787.3 2581.53   795.6 2587.86   804.4  2592.5   872.7 2617.91
#Mann= 7 ,-1,0
       0      .1       0     360     .06       0   455.4      .1       0
  463.57    .045       0  484.42      .1       0   665.5     .06       0
  872.74      .1       0
#XS Ineff= 2 , 0
                          502.53         2549.88
Permanent Ineff=
       F       F
Bank Sta=463.57,484.42
XS Rating Curve= 0 ,0
Exp/Cntr(USF)=0,0
Exp/Cntr=0.3,0.1

Type RM Length L Ch R = 1 ,27446   ,253.4,264.4,269.4
XS GIS Cut Line= 5
2293844.76846854644180.2827540362294225.71467866644214.194879566
2294369.27601007644095.502440212 2294401.1245302644088.082149955
 2294799.9600043644018.634955678
#Sta/Elev= 30
       0 2571.89   119.9 2545.88     152 2529.07   188.1 2516.42   240.8 2515.68
   256.4 2513.99   292.6 2514.95     419 2512.24     422 2511.98  428.012507.703
   433.2 2506.38   448.22507.701   458.3 2511.05   473.9 2510.06   487.2 2513.13
   515.9 2510.47   571.7 2513.43   588.1 2510.73   596.4 2512.03   649.2 2553.89
   677.6 2570.46   697.9 2579.63     706 2585.86   730.4 2589.53   738.5 2596.95
   750.7 2604.84   787.2 2623.21   848.6 2657.39   937.5 2699.57  1006.3 2727.52
#Mann= 9 ,-1,0
       0      .1       0     290     .07       0     300      .1       0
  412.45     .06       0  428.01    .045       0   448.2     .06       0
  532.45      .1       0  641.43     .06       0  741.43      .1       0
#XS Ineff= 2 , 0
                          489.97          2532.3
Permanent Ineff=
       F       F
Bank Sta=428.01,448.2
XS Rating Curve= 0 ,0
Exp/Cntr(USF)=0,0
Exp/Cntr=0.3,0.1

Type RM Length L Ch R = 1 ,27182   ,465,466.2,467.6
XS GIS Cut Line= 4
2293872.11458695644353.4835825052294317.91002683644393.271214829
2294431.52856091644386.1769947362294831.48880968644284.118848137
#Sta/Elev= 30
       0 2558.93    88.4 2532.46   112.5 2530.78   120.5 2525.54   144.6 2519.09
   156.7 2511.91   160.7 2511.38   188.8 2511.83   253.1  2508.7   401.7 2508.75
   421.7 2505.09   477.9 2506.15   501.2 2503.58  505.692501.068   522.6 2499.38
  532.832501.064     546 2515.28     558 2523.12   588.6 2536.88     624 2549.31
   661.4 2571.95   698.3  2579.9   714.8 2590.35   731.3 2591.73   739.6 2598.54
   756.1 2602.31   788.2 2617.14   822.6 2637.37     918 2699.12   974.2 2737.97
#Mann= 7 ,-1,0
       0      .1       0     380     .06       0  477.57      .1       0
  505.69    .045       0  532.83      .1       0  671.41     .06       0
  771.41      .1       0
Bank Sta=505.69,532.83
XS Rating Curve= 0 ,0
Exp/Cntr=0.3,0.1