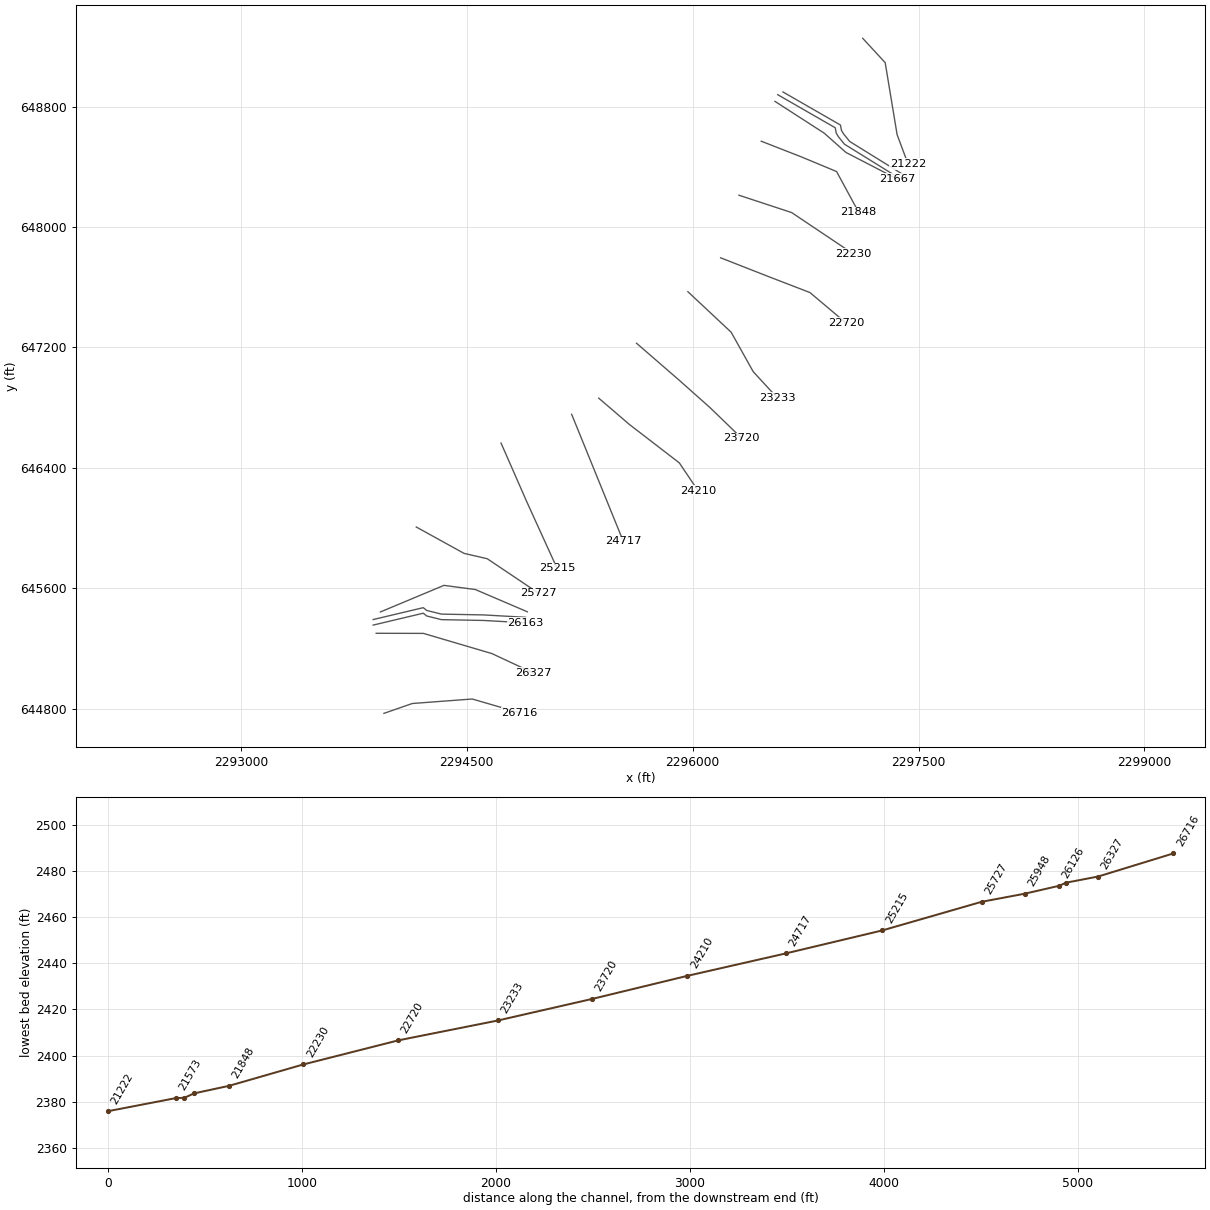
HEC-RAS study RFFILESCK.prj: RFFILESCK

--- RFFILESCK.g01 (geometry) --- (continued)

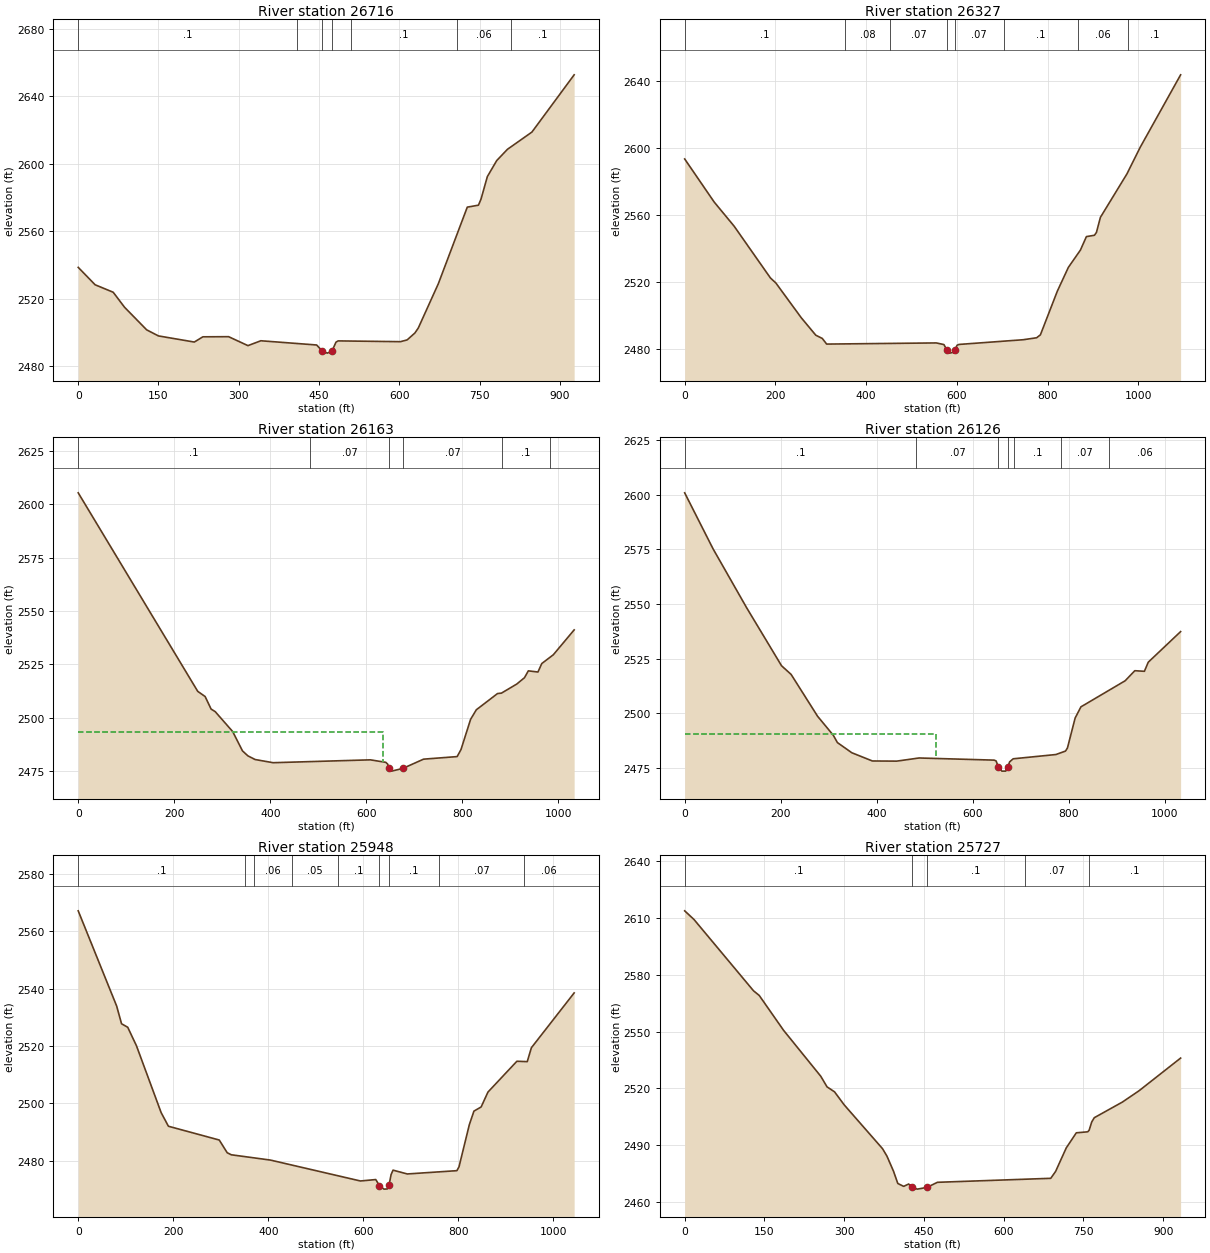
Type RM Length L Ch R = 1 ,26716   ,390.5,388.4,384
XS GIS Cut Line= 4
     2293950.368       644768.18 2294138.6942397644833.757271043
2294536.63512014644863.6583606682294851.93437698644771.955896242
#Sta/Elev= 30
       0  2538.5    31.6 2528.16    65.4 2523.72    86.6 2514.81   127.9 2501.41
   149.9  2497.8   216.9 2494.16     233 2497.26   281.1 2497.34   317.2 2492.03
   341.3 2494.92   445.6 2492.41  456.24 2488.81   465.6 2487.58  474.232488.811
   481.7 2494.08   485.7 2494.84   602.2 2494.38   614.7 2495.43   629.2 2499.54
   635.5 2502.46     673 2528.79   727.1 2574.24     748 2575.41   752.8 2579.07
   764.6 2592.38   782.1 2601.88   802.1 2608.56   847.9 2618.81   926.8 2652.79
#Mann= 7 ,-1,0
       0      .1       0  409.42     .06       0  456.24    .045       0
  474.23     .06       0  509.42      .1       0  708.48     .06       0
  808.48      .1       0
Bank Sta=456.24,474.23
XS Rating Curve= 0 ,0
Exp/Cntr=0.3,0.1

Type RM Length L Ch R = 1 ,26327   ,161.9,164.4,169.1
XS GIS Cut Line= 4
2293899.17427415645300.2838529112294212.86739401 645299.57739287
2294666.92679122645165.6806518592294944.31198001645036.054962897
#Sta/Elev= 30
       0 2593.51      65  2567.8     109 2553.38     189 2522.46     201 2519.45
     257 2498.69     289 2488.28   303.4 2486.32     313 2482.96   554.8 2483.65
   571.5 2482.67  577.832479.525     584 2477.56   592.4 2478.05  595.24 2479.53
   600.7 2482.31   604.9 2482.75   746.4 2485.56   775.9 2486.74   784.2 2488.48
   821.5 2514.55   845.9 2528.79   872.4 2539.09   885.6 2547.14   903.3 2547.94
   907.7 2549.62   916.5 2558.65     975  2584.6  1004.1 2600.43  1093.3 2643.75
#Mann= 8 ,-1,0
       0      .1       0  353.69     .08       0  453.69     .07       0
  577.83    .045       0  595.24     .07       0  703.69      .1       0
  867.08     .06       0  977.08      .1       0
Bank Sta=577.83,595.24
XS Rating Curve= 0 ,0
Exp/Cntr=0.3,0.1

Type RM Length L Ch R = 1 ,26163   ,36.7,37,36.9
XS GIS Cut Line= 6
2293878.97882504645354.7442860572294211.80239638645433.753191265
2294234.67268734 645415.262317722294332.27090296645390.917219955
2294611.78918727645385.5795996612294891.42668467645369.787538253
#Sta/Elev= 30
       0 2605.36   248.9 2512.31   264.3 2509.88   276.7 2504.01   285.4 2502.77
   321.8 2493.42   342.1  2484.4   353.4 2482.06   368.5 2480.34   405.9 2478.86
   608.4  2480.2   640.5 2479.04   644.5 2478.17   647.82476.154   652.5 2474.91
  675.722476.152   719.2 2480.52   789.1 2481.72   797.1 2484.98   817.2 2499.22
   829.1 2503.67   873.3 2511.28   881.3 2511.46   913.3 2515.73   929.3 2518.68
   937.4 2521.91   957.4 2521.37   965.4 2525.34   989.4 2529.45  1032.8 2541.11
#Mann= 6 ,-1,0
       0      .1       0  482.18     .07       0   647.8    .045       0
  675.72     .07       0  882.67      .1       0  982.67     .06       0
#XS Ineff= 2 , 0
          635.36 2493.24
Permanent Ineff=
       F       F
Bank Sta=647.8,675.72
XS Rating Curve= 0 ,0
Exp/Cntr(USF)=0,0
Exp/Cntr=0.3,0.1

Type RM Length L Ch R = 1 ,26126   ,178.6,177.6,176.3
XS GIS Cut Line= 6
2293878.97882504 645391.509765622294211.80239638645470.518670829
2294234.67268734645452.0277972832294332.27090296645427.682699519
2294611.78918727645422.3450792242294891.42668467645406.553017816
#Sta/Elev= 30
       0  2600.8    58.8 2575.31   128.7 2548.37   201.7 2521.73   221.7 2517.75
   276.7 2498.65   309.6  2489.9     318  2486.6     348 2481.94   390.9 2478.17
   441.6  2478.1   488.1 2479.54   644.5 2478.56   648.5 2478.19  653.352475.476
   660.6 2473.53   668.6 2473.54  673.632475.477   676.6 2477.74   684.1 2479.17
   773.1 2481.12   793.1 2482.71   797.1 2484.11   813.2 2497.84   825.2 2502.92
   917.3 2514.85   937.4 2519.45   957.4 2519.18   965.4 2523.34  1032.8 2537.33
#Mann= 7 ,-1,0
       0      .1       0  482.18     .07       0  653.35    .045       0
  673.63     .07       0  685.82      .1       0  782.67     .07       0
  882.67     .06       0
#XS Ineff= 2 , 0
           523.5 2490.36
Permanent Ineff=
       T       F
Bank Sta=653.35,673.63
XS Rating Curve= 0 ,0
Exp/Cntr(USF)=0,0
Exp/Cntr=0.3,0.1

Type RM Length L Ch R = 1 ,25948   ,222.5,220.9,219.6
XS GIS Cut Line= 4
2293927.02453051645441.9372618792294349.08421188645618.688143673
2294557.97161764645590.8364895722294902.90364151645443.008479344
#Sta/Elev= 30
       0  2567.2    80.9 2533.98    91.2  2527.8   104.2 2526.58   122.6 2520.11
   174.5 2496.81   189.8 2492.05   296.8 2487.24   313.5 2482.81   322.2 2482.09
   404.6 2480.24   593.9 2472.95   626.1 2473.45  633.89 2471.34   643.3 2470.11
   650.4 2470.16   653.9 2471.38   658.4 2475.18   662.5 2476.73   692.5  2475.4
   796.9 2476.55   801.3 2477.89     823 2492.57   832.7 2497.32   847.9 2498.78
   862.2 2503.96   923.1 2514.72   944.9 2514.59   953.6 2519.43  1043.6 2538.56
#Mann= 9 ,-1,0
       0      .1       0     350     .05       0     370     .06       0
     450     .05       0  547.58      .1       0  633.89    .045       0
   653.9      .1       0  758.31     .07       0  938.31     .06       0
Bank Sta=633.89,653.9
XS Rating Curve= 0 ,0
Exp/Cntr(USF)=0,0
Exp/Cntr=0.3,0.1

Type RM Length L Ch R = 1 ,25727   ,525,512.1,497.7
XS GIS Cut Line= 4
2294165.40026092646006.3222789552294482.62603888645831.175046492
2294636.34927897645795.6989667662294979.01558918645565.558524652
#Sta/Elev= 30
       0 2613.88    17.6 2609.27   129.5 2571.56   140.2 2569.12   185.9 2550.71
   256.1  2526.3   267.8 2520.73   281.9  2518.1   300.2 2511.16   372.2 2488.01
   380.4 2484.12   392.7  2476.2   400.9 2469.61     412 2468.08   421.4 2469.33
  427.392467.542   437.8 2466.62   455.92467.541   475.4 2470.23   688.6 2472.34
   697.7 2475.96   717.8 2488.44   736.7 2496.42   758.2 2496.95   760.8 2497.77
   765.7 2502.16   770.5 2504.41   823.5 2512.71   854.7 2518.67   932.9 2535.96
#Mann= 5 ,-1,0
       0      .1       0  427.39    .045       0   455.9      .1       0
  640.13     .07       0  760.13      .1       0
Bank Sta=427.39,455.9
XS Rating Curve= 0 ,0
Exp/Cntr=0.3,0.1

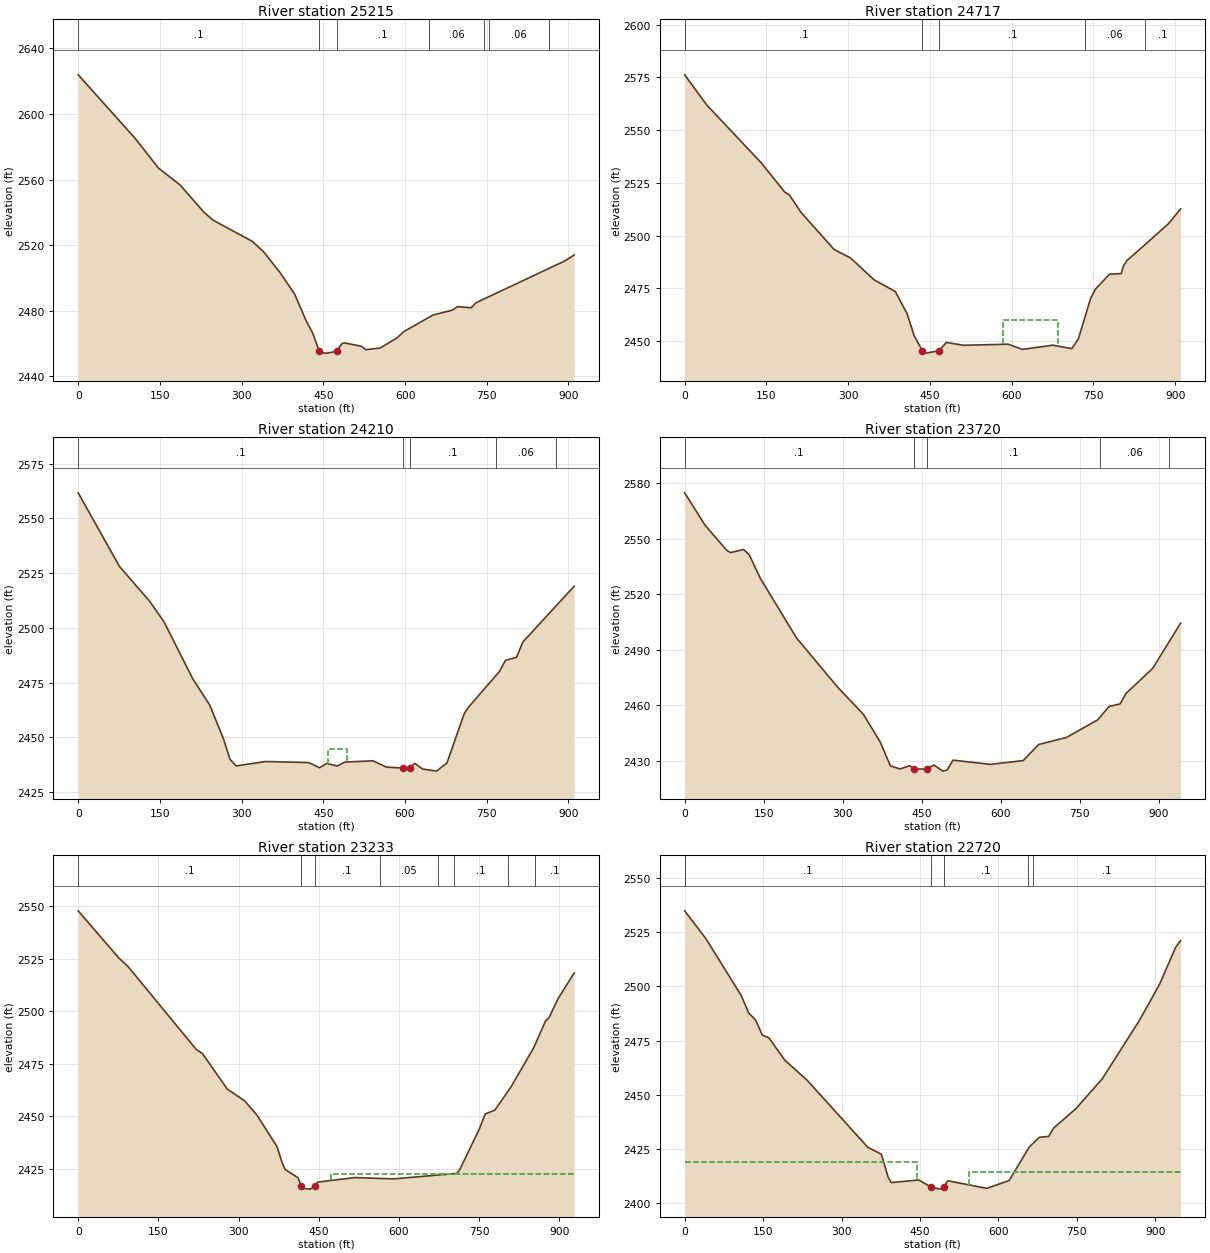
Type RM Length L Ch R = 1 ,25215   ,498.1,497.9,496.7
XS GIS Cut Line= 3
     2294728.008      646564.2482294898.29157489646175.757912977
     2295099.594      645733.206
#Sta/Elev= 30
       0 2623.93   103.8 2585.48   147.5 2567.01   186.8 2556.84   231.1 2540.04
   247.9 2535.26   319.3 2522.43     340 2516.14   370.2 2503.48   397.2 2490.28
   418.3 2474.04   430.6 2466.36   442.42455.401   444.6 2454.33   457.7 2454.22
  474.482455.398   484.1    2460   488.5 2460.47   519.3 2458.47   528.1 2456.33
   554.4 2457.33   585.2 2463.56   598.4 2467.48   651.1 2477.43   686.3  2480.4
   696.4 2482.58   721.4 2481.88   730.2 2484.94   892.7 2510.35   910.4 2514.08
#Mann= 7 ,-1,0
       0      .1       0   442.4    .045       0  474.48      .1       0
  644.17     .06       0  744.17      .1       0  754.17     .06       0
  864.17      .1       0
Bank Sta=442.4,474.48
XS Rating Curve= 0 ,0
Exp/Cntr=0.3,0.1

Type RM Length L Ch R = 1 ,24717   ,504.6,507.8,509.7
XS GIS Cut Line= 3
     2295196.924      646755.206     2295368.204      646333.675
     2295539.484      645912.144
#Sta/Elev= 30
       0 2576.23    40.5 2561.93   140.4 2534.52   183.5 2520.67   192.2 2519.26
   213.8  2510.9   274.2 2493.41   304.4 2489.38   347.6 2479.01   386.5 2473.45
     408 2463.06     421 2452.59  436.162445.398   442.6 2444.25  467.252445.397
   479.9 2449.33   511.7 2447.98   593.7 2448.49   619.6 2446.02   675.7 2448.02
   710.3 2446.38   722.5 2451.09   744.8 2470.13   753.4 2474.47   779.4 2481.67
   800.9 2481.98   805.4 2485.67   811.5 2488.12   887.3 2505.51     910 2512.66
#Mann= 5 ,-1,0
       0      .1       0  436.16    .045       0  467.25      .1       0
     735     .06       0     845      .1       0
#XS Ineff= 1 ,-1
  584.62  684.33 2459.83
Permanent Ineff=
       F
Bank Sta=436.16,467.25
XS Rating Curve= 0 ,0
Exp/Cntr=0.3,0.1

Type RM Length L Ch R = 1 ,24210   ,493.3,489.9,486.4
XS GIS Cut Line= 4
2295376.73457254646862.4882196092295580.24504225646687.855771775
2295911.88937262646432.4214996732296036.58143922646246.715282378
#Sta/Elev= 30
       0 2561.68    75.7 2528.07     131 2512.19   157.4 2502.77   210.4 2476.67
   241.6 2464.67   267.2 2448.94   278.6 2439.93     290 2436.89   343.8 2438.91
   423.3 2438.43     443 2436.05   456.1 2438.05   475.8 2436.84   488.9 2438.63
     541 2439.25     566 2436.35   596.3 2435.93   608.92435.934     618 2438.07
   632.2 2435.49   657.9 2434.52     677 2438.29   708.8 2460.85     716 2463.57
   773.4 2480.08   784.4 2485.14   804.6 2486.49   816.4 2493.53   910.5 2519.01
#Mann= 5 ,-1,0
       0      .1       0   596.3    .045       0   608.9      .1       0
  766.78     .06       0  876.78      .1       0
#XS Ineff= 1 ,-1
  457.79  492.91 2444.75
Permanent Ineff=
       F
Bank Sta=596.3,608.9
XS Rating Curve= 0 ,0
Exp/Cntr=0.3,0.1

Type RM Length L Ch R = 1 ,23720   ,487.5,486.5,478.8
XS GIS Cut Line= 4
     2295627.648      647227.4082295906.12377219646986.012190619
2296115.65213953646799.6392595282296325.87640783646596.342803909
#Sta/Elev= 30
       0 2574.65    38.8 2557.15    80.1 2543.58      87 2542.43   111.9 2544.08
   122.5 2541.27   143.6 2528.55   212.4 2496.33   290.4 2469.84   339.3 2455.17
   371.3 2440.18   390.4 2427.39   408.8 2425.72   427.2 2427.49  434.892425.656
  459.432425.651     473 2427.83   490.2 2424.54   498.1 2425.12   509.4 2430.46
   580.4 2428.18   642.6 2430.23   671.9  2438.9   724.6 2442.68     784 2452.19
   805.5 2459.38   826.5  2460.8   837.8 2466.45   888.4 2479.98   941.4 2504.39
#Mann= 5 ,-1,0
       0      .1       0  434.89    .045       0  459.43      .1       0
  788.96     .06       0  918.96      .1       0
Bank Sta=434.89,459.43
XS Rating Curve= 0 ,0
Exp/Cntr=0.3,0.1

Type RM Length L Ch R = 1 ,23233   ,508.7,513.5,525.8
XS GIS Cut Line= 4
2295968.72287881647569.8117823372296256.00688842647300.655079037
2296402.05142501647038.9473787382296560.55895176646866.614915287
#Sta/Elev= 30
       0 2547.89      76  2525.4    93.4 2521.29   220.8 2481.77   232.1 2479.92
   278.8 2462.89     311 2457.36   334.4 2450.47     372 2435.36   381.2 2427.85
   387.1 2424.53   411.1  2420.6  417.18 2416.77   420.6 2415.57   434.3 2415.19
  442.342416.771     448 2418.55   517.1  2420.7     590 2420.07   708.3 2422.69
   713.1 2424.28   750.1 2443.82   761.2 2451.02   779.2 2452.86   809.4 2463.94
   851.8 2482.57   873.8 2495.27   880.6 2496.97   897.1 2505.87   927.5 2518.27
#Mann= 8 ,-1,0
       0      .1       0  417.18    .045       0  442.34      .1       0
  563.67     .05       0  673.67     .06       0  703.37      .1       0
  803.37     .06       0  853.37      .1       0
#XS Ineff= 2 , 0
                          472.99         2422.48
Permanent Ineff=
       F       F
Bank Sta=417.18,442.34
XS Rating Curve= 0 ,0
Exp/Cntr=0.3,0.1

Type RM Length L Ch R = 1 ,22720   ,490.4,489.3,485.8
XS GIS Cut Line= 4
     2296186.039      647794.9982296515.08889445647665.931914402
2296779.04103644647564.1756867192297017.72365464647363.120094859
#Sta/Elev= 30
       0 2534.73      41 2521.78     108 2495.79   122.6 2487.64   135.8 2484.37
   148.4 2477.53   161.3 2476.21   191.4 2465.96   234.5 2456.64   350.3 2425.82
   376.1 2422.67   388.9 2412.18   395.1  2409.6   447.7 2410.77  470.252407.691
   487.5 2406.57  495.072407.686   503.4 2410.42   577.5 2406.93   620.4  2410.5
   658.7 2425.88   678.2 2430.44   696.1 2430.84   705.8 2434.73   747.7 2443.51
   798.2 2457.26   869.2 2484.11     908 2500.84     939 2517.97   948.4 2521.06
#Mann= 5 ,-1,0
       0      .1       0  470.25    .045       0  495.07      .1       0
  656.34     .06       0  666.34      .1       0
#XS Ineff= 2 , 0
          443.52 2419.07  543.66         2414.23
Permanent Ineff=
       F       F
Bank Sta=470.25,495.07
XS Rating Curve= 0 ,0
Exp/Cntr=0.3,0.1

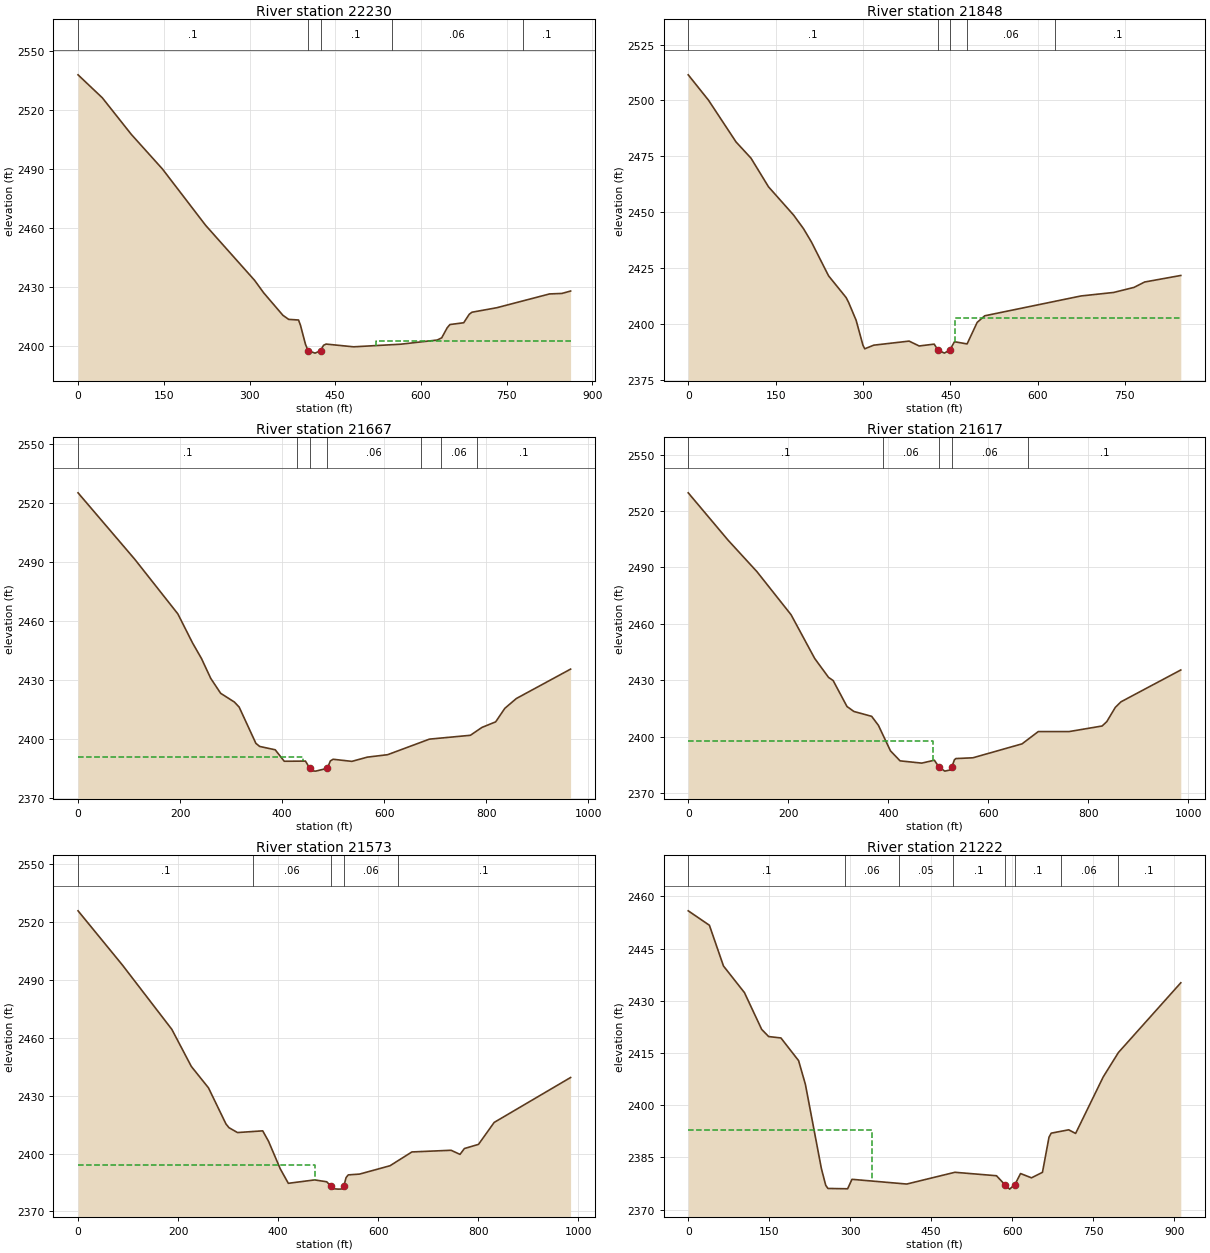
Type RM Length L Ch R = 1 ,22230   ,381.3,382.8,385.3
XS GIS Cut Line= 3
2296307.80045098648210.789650961  2296657.796846648095.482367299
2297067.44410596647820.688235743
#Sta/Elev= 30
       0 2537.76    42.5 2526.06      93 2507.52   147.8  2489.8   223.3 2461.15
   308.9 2433.19   324.7 2426.86   358.4 2415.41   368.5 2413.32   385.8 2412.99
   389.2 2410.31     398 2400.57  402.59 2397.38   414.7 2396.14   424.3 2397.38
   429.5 2400.12     434 2400.75   482.1 2399.35     565 2400.69   628.4  2402.8
   636.3 2403.93   645.9 2409.04   650.7 2410.69   674.8  2411.6   684.4 2415.89
   689.3 2416.96   732.6 2419.24     825 2426.26   846.5 2426.51   861.8 2427.73
#Mann= 5 ,-1,0
       0      .1       0  402.59    .045       0   424.3      .1       0
   548.5     .06       0   778.5      .1       0
#XS Ineff= 2 , 0
                          520.87         2402.52
Permanent Ineff=
       F       F
Bank Sta=402.59,424.3
XS Rating Curve= 0 ,0
Exp/Cntr=0.3,0.1

Type RM Length L Ch R = 1 ,21848   ,182.8,180.8,172.1
XS GIS Cut Line= 4
2296455.74627979648569.7095932712296724.03893315648464.695467588
2296955.97654512648368.1148289132297102.01234807648098.573999442
#Sta/Elev= 30
       0 2511.44    34.8 2500.09    82.1  2481.4   107.8 2474.14   137.9  2461.3
   180.9 2448.68   198.1 2442.53   211.6 2436.61     241 2421.48   271.1 2411.77
   275.4 2409.59   288.3  2401.6   300.1 2390.39   303.1 2388.82   318.6 2390.44
   379.3 2392.26   396.6 2390.08   422.4 2390.91   428.6 2388.36   439.9 2386.88
  449.43 2388.36   457.2 2391.98   478.9    2391   496.2 2400.62   509.2 2403.59
   674.6 2412.47   730.5 2414.03   765.6  2416.3   783.8 2418.71   845.9 2421.64
#Mann= 5 ,-1,0
       0      .1       0   428.6    .045       0  449.43      .1       0
  478.11     .06       0  629.36      .1       0
#XS Ineff= 2 , 0
                          457.84         2402.68
Permanent Ineff=
       F       F
Bank Sta=428.6,449.43
XS Rating Curve= 0 ,0
Exp/Cntr=0.3,0.1

Type RM Length L Ch R = 1 ,21667   ,51.6,50.1,42.6
XS GIS Cut Line= 4
2296546.83962364 648834.398114512296873.66807234648623.261152076
2297018.28243017648495.0364214662297358.60821893648318.606904912
#Sta/Elev= 30
       0 2525.29   111.1  2491.5   195.7 2463.66   224.6 2448.82     242 2440.94
   260.2  2430.8   279.6 2423.23   306.4  2418.8   315.9  2416.2   348.7 2397.73
   356.1 2396.17   386.6 2394.46   404.3 2388.62   445.9 2388.71  454.39 2385.01
   457.5 2383.76     466  2383.6   488.7 2385.03   494.7 2388.79     500 2389.64
   536.9 2388.57   567.1 2390.72     607 2391.97     689 2399.89   769.2 2401.84
   791.8 2405.84   818.8 2408.69   836.8 2415.58   859.3 2420.56   965.7 2435.54
#Mann= 7 ,-1,0
       0      .1       0   429.1     .06       0  454.39    .045       0
   488.7     .06       0  672.37      .1       0  712.37     .06       0
  782.37      .1       0
#XS Ineff= 2 , 0
           440.3 2390.63
Permanent Ineff=
       F       F
Bank Sta=454.39,488.7
XS Rating Curve= 0 ,0
Exp/Cntr(USF)=0,0
Exp/Cntr=0.3,0.1

Type RM Length L Ch R = 1 ,21617   ,39.6,43.6,40.3
XS GIS Cut Line= 6
2296565.08524073648878.8494288332296946.90186207  648659.0988554
2296953.65111637648623.5101364942296968.24917444648599.180039724
2297008.63713507648549.5466423142297361.80221055648330.616065059
#Sta/Elev= 30
       0 2529.63    79.6 2504.47   137.4 2487.71   205.6 2464.81   252.8 2441.59
   280.5 2431.51   289.7 2429.84   317.4 2416.03   331.2  2413.4   366.7  2410.8
   380.2 2406.02   404.3 2392.47   423.5 2387.14   466.9 2385.94     492 2387.48
  501.492383.795   512.8 2381.68   523.6 2382.29  526.932383.798   532.1 2387.69
     535 2388.36   569.1 2388.77   667.4 2396.18   699.8 2402.71   761.5 2402.71
   827.4 2405.67   836.8    2408   853.8 2415.57   865.1 2418.52   984.7 2435.45
#Mann= 5 ,-1,0
       0      .1       0     390     .06       0  501.49    .045       0
  526.93     .06       0  679.13      .1       0
#XS Ineff= 2 , 0
          489.17  2397.8
Permanent Ineff=
       F       F
Bank Sta=501.49,526.93
XS Rating Curve= 0 ,0
Exp/Cntr(USF)=0,0
Exp/Cntr=0.3,0.1

Type RM Length L Ch R = 1 ,21573   ,356.6,351,344.8
XS GIS Cut Line= 6
2296599.85260353648896.9514441732296981.66922487 648677.20087074
2296988.41847917648641.6121518352297003.01653723648617.282055065
2297043.40449787648567.6486576542297396.56957335  648348.7180804
#Sta/Elev= 30
       0 2525.88    88.1 2497.97   187.5 2464.42   226.5 2445.18   260.8 2434.07
   295.7 2415.37   301.8 2413.41   318.8  2410.9   369.2 2411.78   380.9 2406.34
   404.3 2392.07   420.4 2384.58   473.1 2386.34   497.3 2385.36  504.712383.263
   510.3 2381.75   520.3 2381.56   526.5 2381.61  531.542383.261   535.8  2387.5
   540.2 2388.94   562.9 2389.36   623.8  2393.7   667.4 2400.84   745.8 2401.71
   763.6 2399.58   772.4 2402.61   800.6 2404.77   831.9 2416.15   984.7 2439.44
#Mann= 5 ,-1,0
       0      .1       0     350     .06       0  504.71    .045       0
  531.54     .06       0  639.13      .1       0
#XS Ineff= 2 , 0
          473.14 2394.25
Permanent Ineff=
       F       F
Bank Sta=504.71,531.54
XS Rating Curve= 0 ,0
Exp/Cntr(USF)=0,0
Exp/Cntr=0.3,0.1

Type RM Length L Ch R = 1 ,21222   ,508.7,513.9,524.7
XS GIS Cut Line= 4
  2297129.624666649253.2023972362297278.54155731649091.684955722
2297357.97362681648612.612089015 2297430.4600549648418.683623551
#Sta/Elev= 30
       0 2455.88    39.2 2451.73    65.3 2440.01   104.1 2432.37     136  2421.8
     149 2419.73   171.7 2419.33   204.4 2412.81     217 2405.99   246.6  2381.8
   254.6    2377   258.7 2376.06   295.2 2375.97   303.3 2378.69   404.7 2377.33
   493.9 2380.71   570.9 2379.72  586.242377.193   595.3 2375.87   605.1 2377.19
   615.5 2380.35   635.8 2379.12   656.1  2380.7   668.2 2390.79   672.3 2391.96
   704.7 2392.92   717.5 2391.88   768.7 2408.15   796.7 2415.13   912.3 2435.19
#Mann= 8 ,-1,0
       0      .1       0  289.69     .06       0  389.69     .05       0
  489.69      .1       0  586.24    .045       0   605.1      .1       0
  689.69     .06       0   795.3      .1       0
#XS Ineff= 2 , 0
          339.57 2392.82
Permanent Ineff=
       F       F
Bank Sta=586.24,605.1
XS Rating Curve= 0 ,0
Exp/Cntr=0.3,0.1