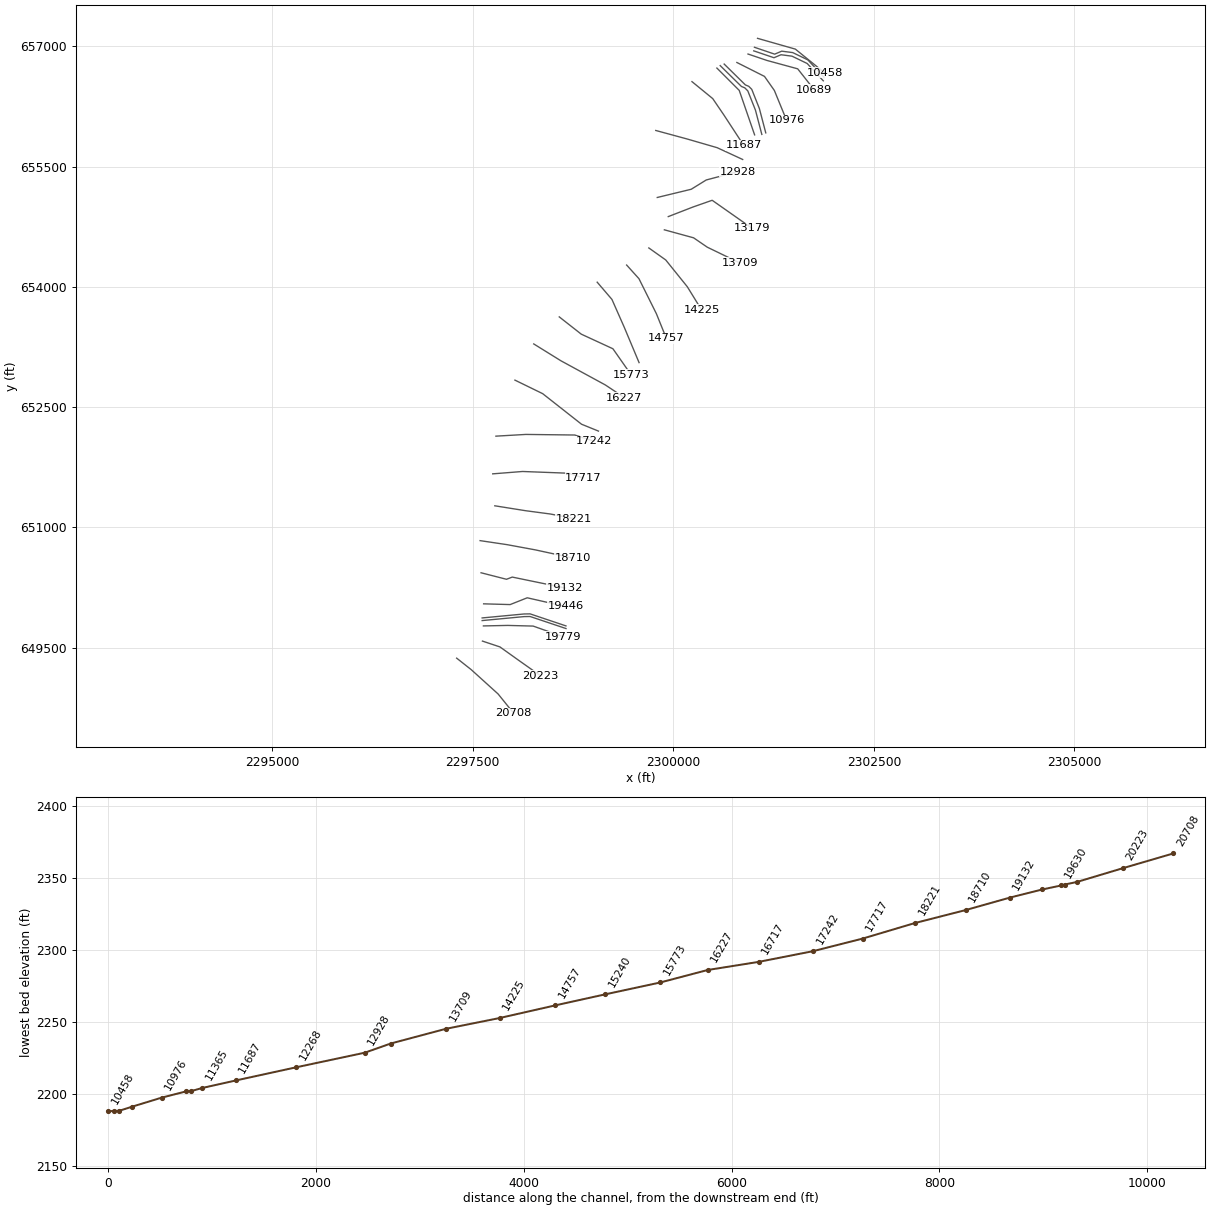
HEC-RAS study RFFILESCK.prj: RFFILESCK

--- RFFILESCK.g01 (geometry) --- (continued)

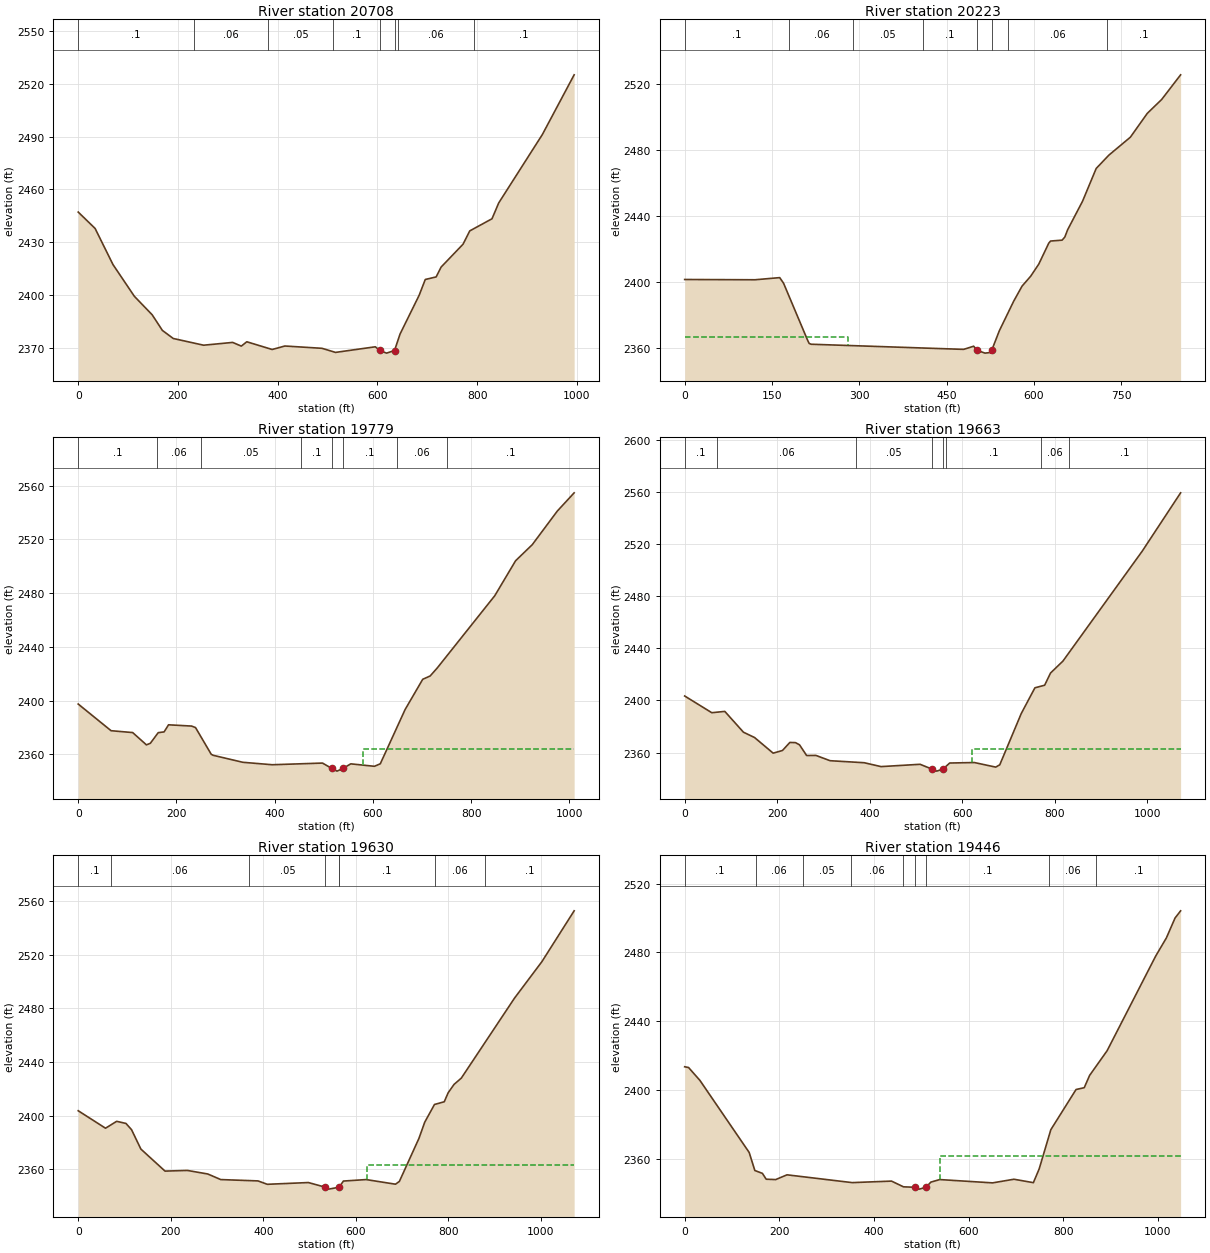
Type RM Length L Ch R = 1 ,20708   ,483.8,484.8,486.9
XS GIS Cut Line= 4
2297299.85802085 649368.424296992297481.27341644649224.933976343
2297816.38413152 648921.484472732298011.57799239648679.523167935
#Sta/Elev= 30
       0 2447.21    33.9 2437.91    69.7 2417.47   112.6 2399.47   148.3    2389
   168.7 2380.17   190.5 2375.58   251.4 2371.77   309.6 2373.35     327 2371.26
     338 2373.71   388.9 2369.34   414.4 2371.31   488.8 2370.01   515.8 2367.69
   595.7 2370.87  604.292368.783   618.3 2367.28  634.142368.763   645.3 2378.12
   683.5 2400.03   695.8    2409   717.6 2410.46   727.6 2416.04   771.6 2429.02
     785 2436.54   829.6 2443.41   843.1 2452.39   930.5 2491.11   994.3 2524.97
#Mann= 8 ,-1,0
       0      .1       0   231.3     .06       0   381.3     .05       0
   511.3      .1       0  604.29    .045       0  634.14      .1       0
   641.3     .06       0  793.39      .1       0
Bank Sta=604.29,634.14
XS Rating Curve= 0 ,0
Exp/Cntr=0.3,0.1

Type RM Length L Ch R = 1 ,20223   ,440.2,444.4,454.3
XS GIS Cut Line= 4
2297621.26296352649581.1316023522297839.13814221649508.504585806
2298088.23370846649330.4536931552298346.75451764649147.941868251
#Sta/Elev= 30
       0 2401.63   121.1 2401.47   163.3 2402.77   169.9 2399.42     211 2365.08
   213.9 2362.93   217.3 2362.44   479.4 2359.33   496.6 2361.25  502.932358.696
   516.1 2357.06   524.3 2357.39  527.592358.698   540.7 2370.55   565.4 2388.48
   579.8 2397.61   594.5 2403.56   608.5 2410.91   625.7 2423.63   628.8 2424.91
   648.7 2425.45   653.3 2427.33   658.2 2431.78   683.7 2448.97   707.2 2468.84
     729 2476.91   765.9 2487.76     795 2502.19   819.8 2510.63   852.3 2525.53
#Mann= 8 ,-1,0
       0      .1       0     180     .06       0  289.66     .05       0
  409.66      .1       0  502.93    .045       0  527.59      .1       0
  555.85     .06       0  725.85      .1       0
#XS Ineff= 2 , 0
          280.73 2366.71
Permanent Ineff=
       F       F
Bank Sta=502.93,527.59
XS Rating Curve= 0 ,0
Exp/Cntr=0.3,0.1

Type RM Length L Ch R = 1 ,19779   ,115.6,116.2,116.6
XS GIS Cut Line= 4
2297633.28284249649770.3381603232297937.52328458649776.630571144
2298253.16846217649768.3834375472298620.57424289649638.239713433
#Sta/Elev= 30
       0 2397.41    66.9 2377.55   110.9 2376.16   138.9    2367   146.9 2368.19
   162.9 2376.09   174.9 2376.66   183.9 2381.94   230.9    2381   238.9 2379.87
   270.9 2359.95     275 2359.21     335 2354.03     395  2352.2   497.4 2353.44
  516.39 2349.44     527 2347.44  539.012349.441     555 2352.86   603.1 2351.04
   615.1 2352.91   665.7 2393.38   701.5 2415.85   716.6 2418.31   731.5 2424.48
   848.2 2478.11   890.6 2504.16   924.5 2516.11   975.5 2541.14  1009.8 2554.74
#Mann= 8 ,-1,0
       0      .1       0     160     .06       0     250     .05       0
  454.31      .1       0  516.39    .045       0  539.01      .1       0
  650.06     .06       0  750.06      .1       0
#XS Ineff= 2 , 0
                          579.73         2364.04
Permanent Ineff=
       F       F
Bank Sta=516.39,539.01
XS Rating Curve= 0 ,0
Exp/Cntr=0.3,0.1

Type RM Length L Ch R = 1 ,19663   ,32.8,32.9,33.4
XS GIS Cut Line= 4
2297617.84659663649837.0519104452298139.75420853649886.495789468
2298215.55483866649887.7301268822298662.69304462649737.663578639
#Sta/Elev= 30
       0 2403.43    58.6 2390.58    86.7 2391.59     127  2375.6     151 2371.52
   191.2  2359.5   211.3 2361.55   227.3 2367.73   239.4  2367.6   248.2  2365.9
   263.5 2357.69   283.6 2357.77   314.2  2353.7   388.1 2352.14   424.3 2349.16
   508.7 2350.94  534.242347.268   544.7 2345.69  558.172347.266   572.7 2351.92
     626 2352.29   672.1 2348.78   680.9 2350.56   727.3 2389.92   756.8  2409.7
   777.9 2411.71   790.6 2421.08   817.4 2430.25   988.9 2514.81  1071.7 2559.55
#Mann= 8 ,-1,0
       0      .1       0      70     .06       0     370     .05       0
  534.24    .045       0  558.17     .05       0  564.24      .1       0
  770.06     .06       0  830.06      .1       0
#XS Ineff= 2 , 0
                          621.56          2362.9
Permanent Ineff=
       F       F
Bank Sta=534.24,558.17
XS Rating Curve= 0 ,0
Exp/Cntr(USF)=0,0
Exp/Cntr=0.3,0.1

Type RM Length L Ch R = 1 ,19630   ,180.1,184.1,189.6
XS GIS Cut Line= 4
2297617.40865489649869.8975410852298139.31626679649919.341420107
2298215.11689692649920.5757575222298662.25510287649770.509209278
#Sta/Elev= 30
       0 2403.56      59 2390.52    83.1 2395.66   103.2 2394.08   115.3 2389.39
   135.4 2374.96   187.6  2358.5   235.8    2359     280 2356.35   308.1 2352.18
   388.5 2351.18   408.6 2348.65   497.4 2349.96  534.242346.457   541.1 2345.05
  563.742346.458   573.1 2351.08   622.3 2352.18   685.6 2348.73     694 2350.79
   736.3 2382.93   748.8 2395.01   769.9 2408.24     791 2410.26   799.4 2416.95
   812.1  2423.2   827.9 2427.93   942.9 2487.66    1002 2514.85  1071.7 2552.79
#Mann= 8 ,-1,0
       0      .1       0      70     .06       0     370     .05       0
  534.24    .045       0  563.74     .05       0  564.24      .1       0
  770.06     .06       0  880.06      .1       0
#XS Ineff= 2 , 0
                          624.68         2362.74
Permanent Ineff=
       F       F
Bank Sta=534.24,563.74
XS Rating Curve= 0 ,0
Exp/Cntr(USF)=0,0
Exp/Cntr=0.3,0.1

Type RM Length L Ch R = 1 ,19446   ,315.2,314.3,313.5
XS GIS Cut Line= 4
2297635.96461975650045.7972259392297966.58729426650036.539791053
2298179.50829665650121.1791957282298655.60494795650012.734958488
#Sta/Elev= 30
       0 2413.43     8.2    2413    32.2 2405.51   136.3 2363.59   148.3 2353.08
   164.3 2351.41   172.3 2348.01   192.3 2347.79   216.3 2350.56     354 2346.03
   437.2 2346.91   462.4 2343.58   487.4 2343.32     496 2342.24  509.94  2343.3
   520.4 2346.33   539.1  2347.8   650.8 2345.88   695.9 2347.99     737    2346
   749.3 2354.04   773.9 2376.82   827.2  2400.2   844.5 2401.26   855.9 2408.42
   892.9 2422.79   995.4 2477.78  1018.2 2488.44  1036.4 2499.96  1048.2 2504.16
#Mann= 9 ,-1,0
       0      .1       0     150     .06       0     250     .05       0
  350.75     .06       0  460.75      .1       0   487.4    .045       0
  509.94      .1       0  769.88     .06       0  869.88      .1       0
#XS Ineff= 2 , 0
                          539.78          2361.5
Permanent Ineff=
       F       F
Bank Sta=487.4,509.94
XS Rating Curve= 0 ,0
Exp/Cntr(USF)=0,0
Exp/Cntr=0.3,0.1

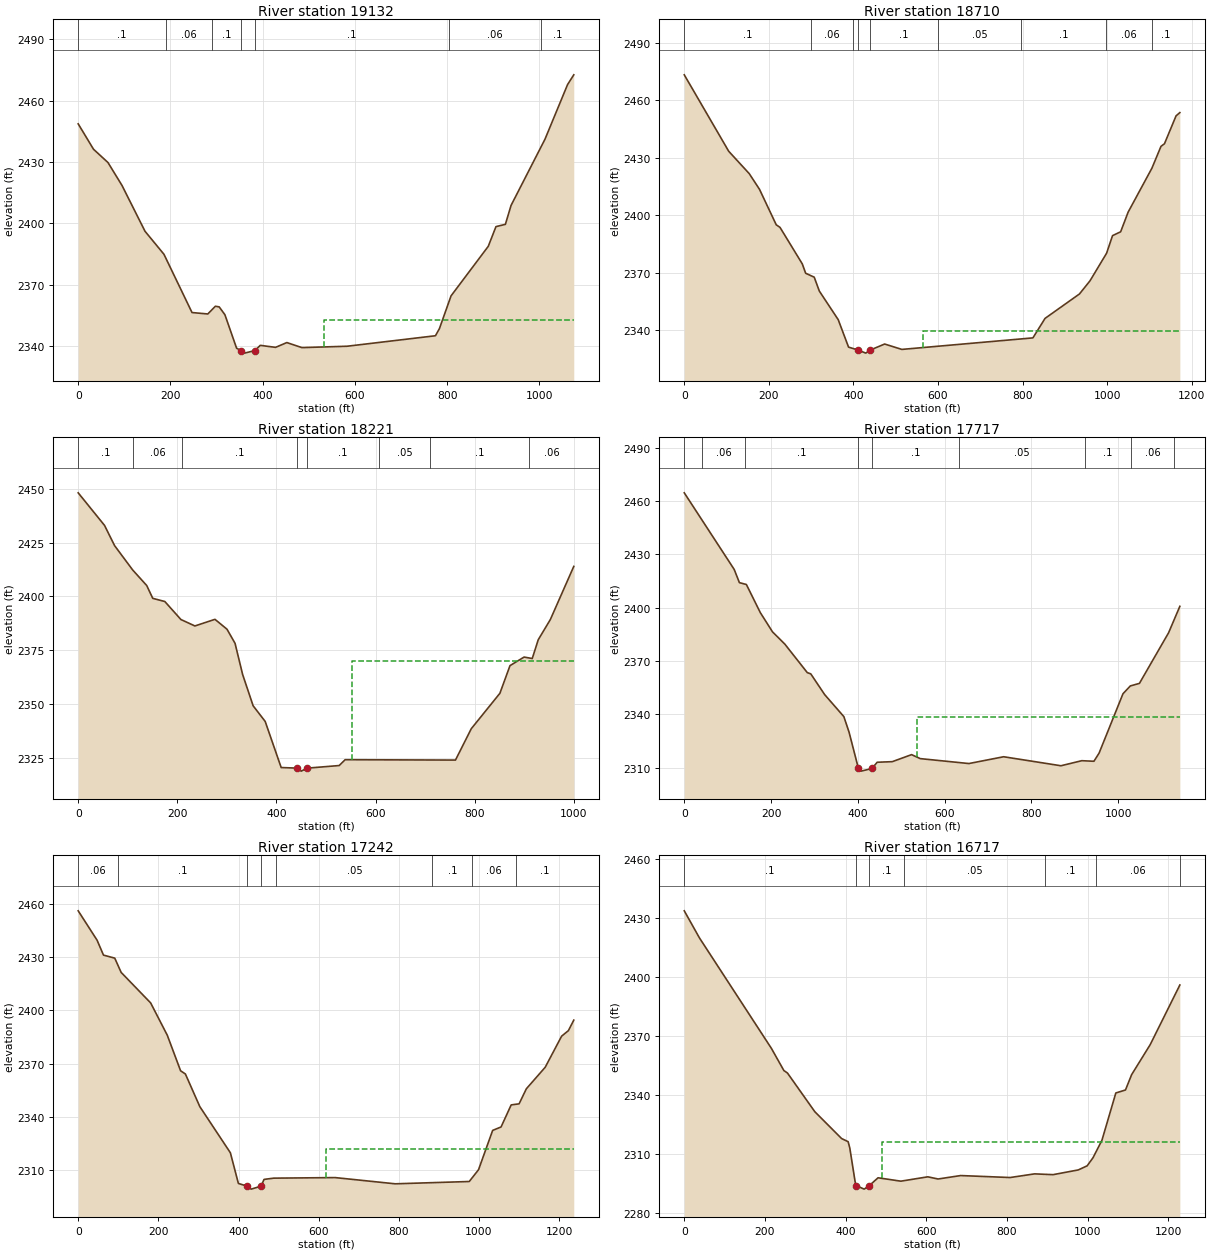
Type RM Length L Ch R = 1 ,19132   ,429.3,421.3,413.3
XS GIS Cut Line= 4
2297603.97346899650433.1878809892297920.87768279650352.122923841
 2297993.0084531 650379.508490152298649.44668792650244.050566862
#Sta/Elev= 30
       0 2448.64    33.2 2436.23    64.6 2429.72    95.2 2418.44   144.8 2396.15
     186 2384.85   246.8 2356.38     281 2355.68   297.5 2359.47   305.7 2359.15
   318.1 2355.32   343.5 2338.91   353.62337.797   360.6 2336.54  383.01 2337.78
   394.8 2340.34   427.9 2339.36   452.4  2341.7   485.1 2339.23   583.1 2339.91
   774.6 2345.04   783.2 2348.52   808.4 2364.53   889.1 2388.76   905.8 2398.39
   926.2 2399.51   938.5 2408.75    1012  2441.1    1061 2467.82  1074.5 2472.61
#Mann= 7 ,-1,0
       0      .1       0     190     .06       0     290      .1       0
   353.6    .045       0  383.01      .1       0  804.26     .06       0
 1004.26      .1       0
#XS Ineff= 2 , 0
                          533.97         2352.65
Permanent Ineff=
       F       F
Bank Sta=353.6,383.01
XS Rating Curve= 0 ,0
Exp/Cntr=0.3,0.1

Type RM Length L Ch R = 1 ,18710   ,491,489.7,489.3
XS GIS Cut Line= 4
2297592.22771706650834.086710583 2297928.2101054650783.932888121
2298279.41427654650719.1178903762298743.72080216650618.165907991
#Sta/Elev= 30
       0 2473.31   105.1 2433.39   153.6 2421.72   177.9 2413.53   217.5 2394.99
   226.4 2393.64     279 2374.62   287.1 2369.67   307.3 2367.65   319.4 2360.38
   364.1 2345.44   388.5 2331.11  411.312329.556   429.2 2327.97  439.652329.554
   473.9 2332.72   514.6 2329.91   824.5 2335.93   853.2 2346.11   934.5 2358.85
   959.6 2365.76   998.7 2380.13  1012.8 2389.33    1032 2391.34  1049.7  2401.6
    1106 2424.58  1127.4 2435.96  1135.6 2437.32  1163.1 2451.91    1172 2453.58
#Mann= 9 ,-1,0
       0      .1       0     300     .06       0  399.71      .1       0
  411.31    .045       0  439.65      .1       0  599.71     .05       0
  796.84      .1       0  996.84     .06       0 1106.84      .1       0
#XS Ineff= 2 , 0
                          564.24         2339.69
Permanent Ineff=
       F       F
Bank Sta=411.31,439.65
XS Rating Curve= 0 ,0
Exp/Cntr=0.3,0.1

Type RM Length L Ch R = 1 ,18221   ,502.5,503.2,502.5
XS GIS Cut Line= 4
2297775.59697365651268.5994803452298157.17576754651207.680018597
 2298468.1922922651166.210749735 2298762.4973791 651109.18259258
#Sta/Elev= 30
       0 2448.08    53.2 2432.95    73.5 2423.56     110 2412.27   138.3 2405.06
   150.5 2399.11   174.8 2397.65   207.2  2389.3   235.5  2386.3     276 2389.38
   300.3 2384.78   316.5 2378.25   331.8 2363.79     353 2349.26   377.3 2342.01
   409.6  2320.6  441.722320.339     450 2318.94  462.332320.332   526.6 2321.53
   538.7 2324.24   761.3 2324.07   793.2 2338.63   850.9 2355.05   871.3 2367.89
   899.8 2371.87   916.2 2371.19   928.3 2379.91   952.8 2389.31    1000 2413.94
#Mann= 8 ,-1,0
       0      .1       0     110     .06       0     210      .1       0
  441.72    .045       0  462.33      .1       0  606.41     .05       0
  710.18      .1       0  910.18     .06       0
#XS Ineff= 2 , 0
                          552.35         2369.82
Permanent Ineff=
       F       F
Bank Sta=441.72,462.33
XS Rating Curve= 0 ,0
Exp/Cntr=0.3,0.1

Type RM Length L Ch R = 1 ,17717   ,472.7,475.4,474
XS GIS Cut Line= 4
2297749.44509805651667.1670117592298122.04986517651696.678004649
2298697.46335574651674.7910824722298880.76692055651615.088753589
#Sta/Elev= 30
       0 2464.55   115.1  2421.5   127.1 2414.06   143.2 2413.03   175.3 2397.22
   203.4 2386.41   231.5 2379.62   283.6  2363.5   291.6 2362.81   323.7 2351.13
   367.9 2338.77   379.9 2330.02  401.462309.639   407.9 2308.14  432.792309.641
   444.7 2313.13   479.5 2313.46     524 2317.41     544 2315.17   656.1  2312.4
   736.2 2316.22   868.3 2311.16   916.3    2314   944.3 2313.68   956.2 2318.24
  1011.3 2351.63  1028.2 2356.02  1049.2 2357.45  1116.5 2385.93  1142.4 2400.76
#Mann= 9 ,-1,0
       0      .1       0      40     .06       0     140      .1       0
  401.46    .045       0  432.79      .1       0  633.77     .05       0
  923.77      .1       0  1029.6     .06       0  1129.6      .1       0
#XS Ineff= 2 , 0
                          535.43         2338.46
Permanent Ineff=
       F       F
Bank Sta=401.46,432.79
XS Rating Curve= 0 ,0
Exp/Cntr=0.3,0.1

Type RM Length L Ch R = 1 ,17242   ,538.3,525.4,516.1
XS GIS Cut Line= 4
2297789.14204184 652137.321809382298162.45973964652158.888911664
2298771.54285566652151.5390987212299013.02520416652074.666632709
#Sta/Elev= 30
       0 2456.09    47.1 2439.57    63.1 2431.16    91.2 2429.46   107.2 2421.43
   180.8 2404.25   222.4 2386.01   255.5 2366.05   267.5 2364.24   303.5 2345.86
   379.7 2319.91   399.7 2302.63  421.482301.132   431.7 2299.44  456.31 2301.13
   463.7 2304.91   487.7 2305.62   641.2 2305.93     791 2302.43   975.7 2303.73
   998.9 2310.38  1034.1  2332.5  1055.1 2334.43  1080.3 2346.84  1100.1 2347.45
  1118.1  2355.9  1165.2 2368.04  1206.2 2385.55    1223 2388.63  1236.5 2394.56
#Mann= 8 ,-1,0
       0     .06       0     100      .1       0  421.48    .045       0
  456.31      .1       0  493.94     .05       0  883.94      .1       0
  983.07     .06       0 1093.07      .1       0
#XS Ineff= 2 , 0
                           619.3         2321.82
Permanent Ineff=
       F       F
Bank Sta=421.48,456.31
XS Rating Curve= 0 ,0
Exp/Cntr=0.3,0.1

Type RM Length L Ch R = 1 ,16717   ,486.6,489.8,491.6
XS GIS Cut Line= 4
2298026.29586052652836.0996977982298371.94383263652667.378134829
2298856.34905929652286.1916698812299067.13912977652200.531507179
#Sta/Elev= 30
       0 2433.74    37.7 2419.92     216 2363.68   246.9 2352.39   255.8 2351.12
   323.6 2331.42     390 2317.74   406.3 2316.13   410.4 2312.89   423.4 2295.94
  425.972293.781     446 2291.97  458.88 2293.78   480.4 2297.75     537 2296.02
   603.8 2298.24   629.2 2297.13   685.2 2298.88   807.9 2297.88   868.5 2299.74
   914.3 2299.34   976.8 2301.75   998.8 2303.84  1013.4    2308  1035.4 2316.84
  1069.9 2340.96  1093.8 2342.47  1109.1  2350.3  1155.2 2365.61  1228.6 2395.95
#Mann= 7 ,-1,0
       0      .1       0  425.97    .045       0  458.88      .1       0
  544.63     .05       0  894.63      .1       0 1021.03     .06       0
 1228.56      .1       0
#XS Ineff= 2 , 0
                          489.59         2316.04
Permanent Ineff=
       F       F
Bank Sta=425.97,458.88
XS Rating Curve= 0 ,0
Exp/Cntr=0.3,0.1

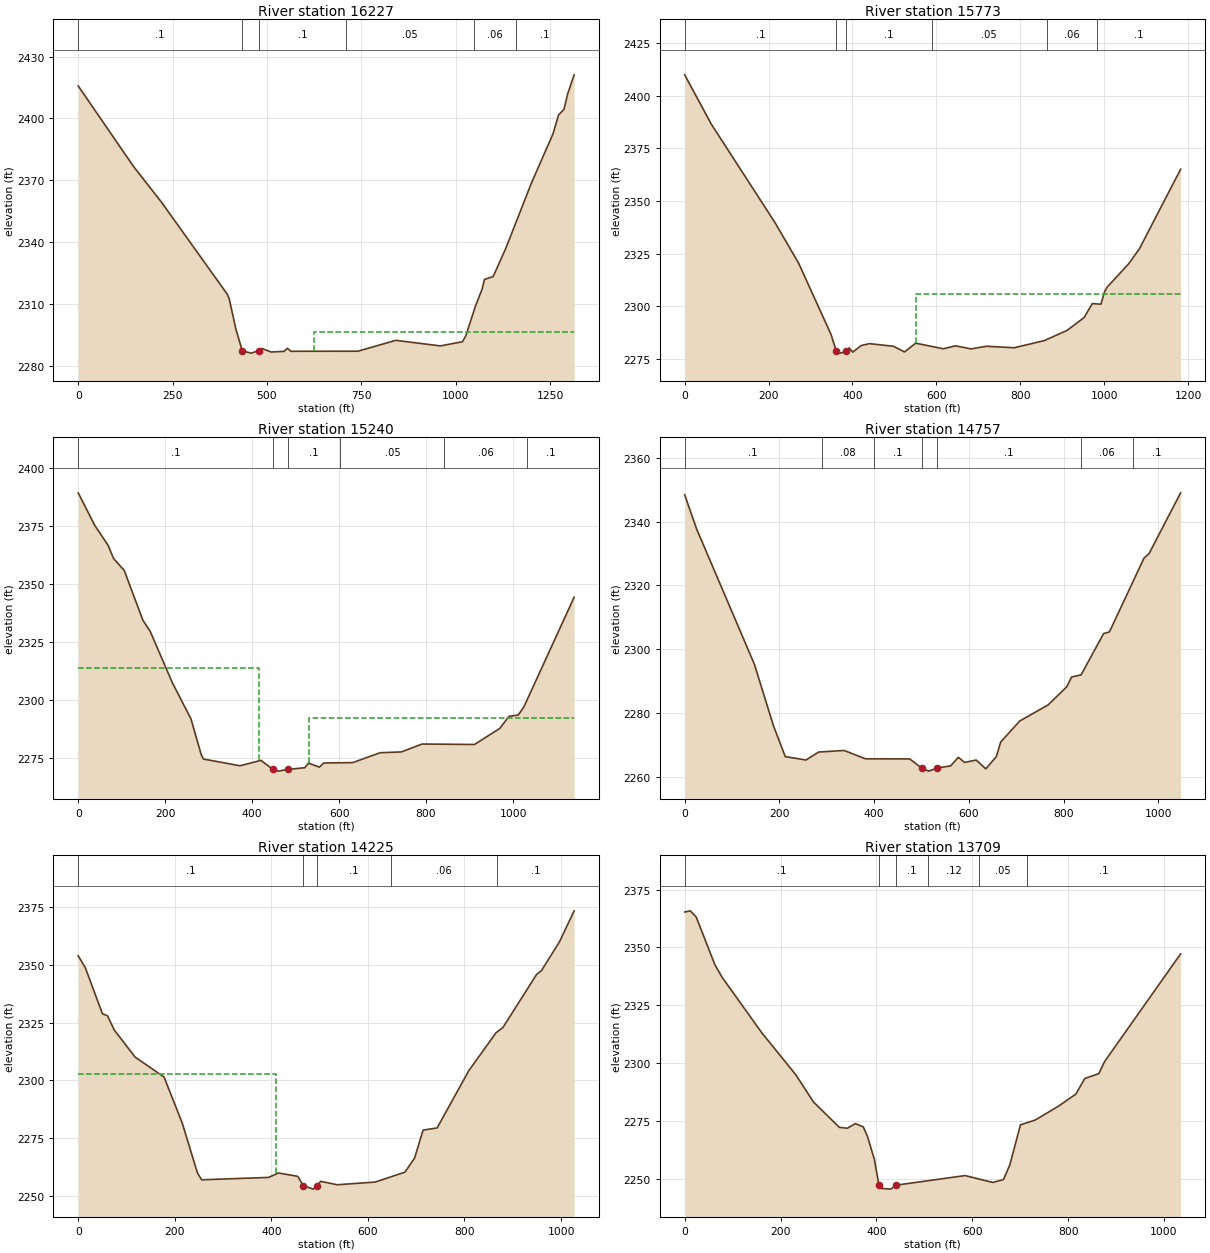
Type RM Length L Ch R = 1 ,16227   ,454.5,454.2,451
XS GIS Cut Line= 4
     2298260.761      653287.5442298600.48656587653076.747144709
2299152.86193757652776.0533516422299390.52355206 652618.13398056
#Sta/Elev= 30
       0 2415.78   146.5 2376.78   220.6 2359.47   394.7 2314.96   399.8 2312.91
   417.7 2298.07  434.692287.486   458.2 2286.35   478.9 2287.54     486 2288.63
   511.3 2286.89   545.2  2287.2   554.3 2288.69   563.4 2287.24     741 2287.28
   841.6 2292.54   959.6 2289.85    1018 2291.86  1027.4 2294.85  1051.9 2308.79
  1070.1  2317.3  1076.5 2322.06  1099.6 2323.46  1133.6 2337.38  1200.5 2368.56
    1258 2392.53  1272.8 2401.72  1287.1 2404.42  1296.8 2411.84  1314.1 2421.15
#Mann= 6 ,-1,0
       0      .1       0  434.69    .045       0   478.9      .1       0
  709.81     .05       0 1048.73     .06       0 1158.73      .1       0
#XS Ineff= 2 , 0
                          625.36          2296.5
Permanent Ineff=
       F       F
Bank Sta=434.69,478.9
XS Rating Curve= 0 ,0
Exp/Cntr=0.3,0.1

Type RM Length L Ch R = 1 ,15773   ,536.4,532.6,516.2
XS GIS Cut Line= 4
2298578.68282743653624.8953450642298853.00907905653409.517940821
2299247.54727593 653227.373523942299476.16793391652900.604434555
#Sta/Elev= 30
       0 2409.99    63.5 2386.53   215.5 2339.68   271.6 2320.46   348.8 2286.62
   361.1 2278.83   372.5 2277.71   384.6 2278.81   391.9 2280.19   400.7  2278.2
   420.7  2281.3   440.4 2282.22   497.6 2280.97   524.1 2278.29   550.5 2282.44
   616.6 2279.78   645.4 2281.19   682.7 2279.72   719.1 2280.98   785.4 2280.26
   857.2 2283.67   911.7 2288.54     952  2294.6   971.5 2301.24   992.2 2300.97
  1000.7 2306.81  1006.5 2308.98  1058.2 2320.16  1083.8 2327.26  1182.1  2365.1
#Mann= 6 ,-1,0
       0      .1       0   361.1    .045       0   384.6      .1       0
  588.77     .05       0  863.33     .06       0  983.33      .1       0
#XS Ineff= 2 , 0
                           551.5         2305.73
Permanent Ineff=
       F       F
Bank Sta=361.1,384.6
XS Rating Curve= 0 ,0
Exp/Cntr=0.3,0.1

Type RM Length L Ch R = 1 ,15240   ,480.1,483,478.7
XS GIS Cut Line= 4
2299051.44560276654057.8645553342299235.38786462653842.776187258
2299388.66886048653495.848266653 2299573.4048419653054.688467385
#Sta/Elev= 30
       0  2389.3    37.9 2375.32    69.1 2366.58    81.1 2361.09     106 2355.82
   148.8  2334.4   165.6 2329.61   216.7 2307.43   259.2 2291.99     283 2276.47
   287.9 2274.64   372.2 2271.74   420.3 2274.06  447.93 2270.17   460.7 2269.43
   481.5 2270.17   520.9 2270.89   529.7 2272.86   554.8 2271.16   564.6 2272.93
   631.4  2273.1   694.5 2277.36   743.2  2277.7     791  2281.1   911.5 2280.91
   969.6 2287.84   990.4    2293  1012.1 2293.62  1025.1 2297.13  1140.6 2344.33
#Mann= 6 ,-1,0
       0      .1       0  447.93    .045       0   481.5      .1       0
  603.02     .05       0   842.3     .06       0  1032.3      .1       0
#XS Ineff= 2 , 0
          415.89 2313.76  530.67         2292.41
Permanent Ineff=
       F       F
Bank Sta=447.93,481.5
XS Rating Curve= 0 ,0
Exp/Cntr=0.3,0.1

Type RM Length L Ch R = 1 ,14757   ,527.6,532,535.4
XS GIS Cut Line= 4
2299418.56596069654271.4962302382299572.15161209654101.251512746
2299789.21519937 653664.788919512299913.14753952 653358.48699352
#Sta/Elev= 30
       0 2348.43    25.4 2337.62   147.2 2295.26   187.5 2275.94   212.4 2266.28
   256.2 2265.22     283 2267.72   336.6 2268.21     382 2265.59   475.1 2265.56
  500.67  2262.7   515.3 2261.73   533.1 2262.69   561.7 2263.38   577.8 2266.06
   591.2 2264.46   615.6 2265.21   635.9 2262.44   658.2 2266.32   667.2 2270.84
   707.4 2277.45   767.3 2282.49   806.9  2288.2     817 2291.26   837.1 2291.92
   884.6 2304.88   896.9  2305.4   969.9 2328.55   980.6 2329.96  1047.2 2349.03
#Mann= 7 ,-1,0
       0      .1       0  289.29     .08       0  399.29      .1       0
  500.67    .045       0   533.1      .1       0  836.74     .06       0
  946.74      .1       0
Bank Sta=500.67,533.1
XS Rating Curve= 0 ,0
Exp/Cntr=0.3,0.1

Type RM Length L Ch R = 1 ,14225   ,507.6,516.5,516.6
XS GIS Cut Line= 4
2299695.25091504654484.7248583972299905.81339516654335.047645812
2300174.64031819654001.0895825042300352.99444022653711.443368076
#Sta/Elev= 30
       0 2353.86    14.7 2348.72    50.2 2328.78    60.6 2327.93    74.7 2321.78
   117.9 2310.07   177.8 2301.45   215.5 2281.55     247 2259.98   255.6 2257.04
   394.2 2258.07     415 2259.99   454.8 2258.52  465.992254.542   486.7 2253.01
  494.992254.539   502.1 2256.38   536.4  2254.9   615.1 2256.06   676.7 2260.34
   696.8 2266.47   714.3 2278.51   743.4 2279.46   809.1 2304.23   865.4 2320.59
   879.5  2322.8   949.4 2345.78   959.4 2347.41     997 2359.97  1027.2 2373.28
#Mann= 5 ,-1,0
       0      .1       0  465.99    .045       0  494.99      .1       0
  648.34     .06       0  867.05      .1       0
#XS Ineff= 2 , 0
          409.82 2302.96
Permanent Ineff=
       F       F
Bank Sta=465.99,494.99
XS Rating Curve= 0 ,0
Exp/Cntr=0.3,0.1

Type RM Length L Ch R = 1 ,13709   ,511.6,529.4,540.1
XS GIS Cut Line= 4
2299888.80139279654711.0071106682300253.12544794654611.184185445
2300423.60805873654494.3295542332300828.96729099654297.991268194
#Sta/Elev= 30
       0 2365.32    11.8 2365.83    24.2  2363.1    62.8 2342.64    78.2 2337.07
   161.1 2313.06   231.6 2295.03   268.9 2283.17   322.8 2272.23   339.4 2271.83
     356 2273.84   372.6 2272.45   381.4 2268.31   395.8 2258.38  405.322247.261
   409.6 2245.86   429.9 2245.52  441.91 2247.26   585.1 2251.38   642.8 2248.41
   665.1 2249.64   678.4 2255.96   700.6  2273.3   731.7 2275.41   780.6 2281.47
   816.3 2286.62   834.8 2293.34   864.2 2295.47   876.2 2300.67  1034.8 2347.22
#Mann= 6 ,-1,0
       0      .1       0  405.32    .045       0  441.91      .1       0
  507.75     .12       0  614.44     .05       0  714.44      .1       0
Bank Sta=405.32,441.91
XS Rating Curve= 0 ,0
Exp/Cntr=0.3,0.1

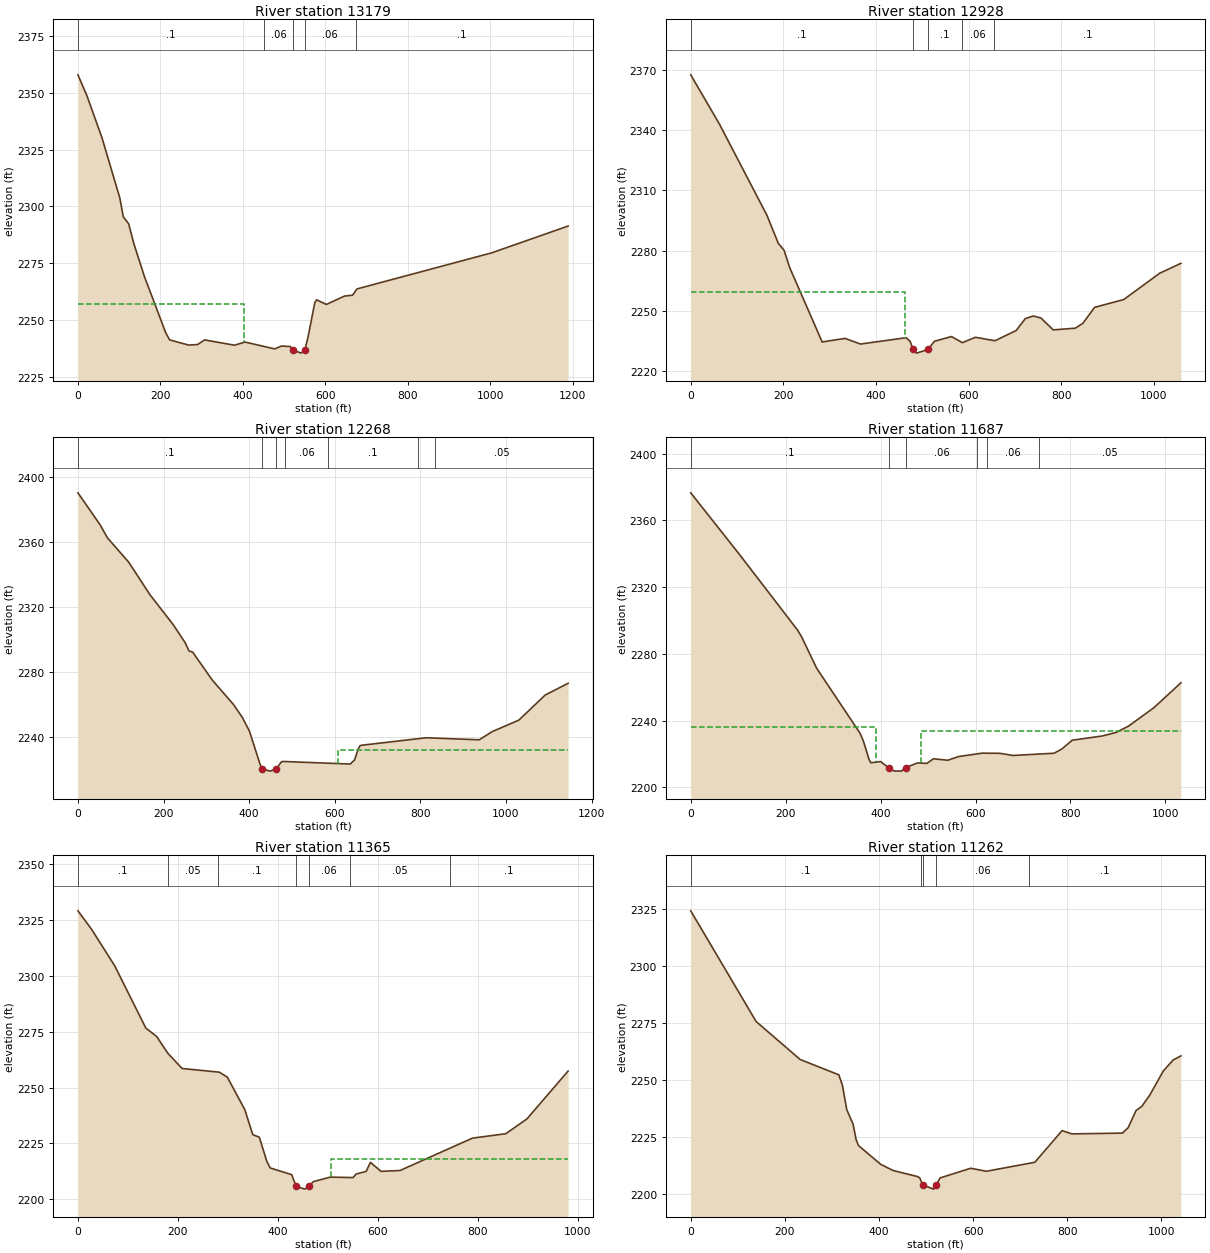
Type RM Length L Ch R = 1 ,13179   ,246.5,251.1,251.5
XS GIS Cut Line= 4
2299937.52724605 654875.834948122300246.26379176654995.740903003
2300484.64530339655079.3571160582300980.00774259654731.358061248
#Sta/Elev= 30
       0 2358.05    21.6 2348.96    58.6 2330.15   101.5 2303.85   110.1 2295.44
     123 2292.39     136 2283.41   161.6 2268.99   213.1 2244.28   222.5 2241.18
   268.9 2238.88   290.5 2239.14   307.5 2241.17   379.9 2238.83   405.3 2240.22
   477.4 2237.21   493.9 2238.47   515.5 2238.24  522.852236.764   540.9 2235.34
  550.562236.763   557.9  2242.1   574.8 2257.66   579.1 2258.84   602.8  2256.8
   646.8  2260.5   666.4 2260.89   676.9 2263.64  1003.7 2279.55  1189.2 2291.37
#Mann= 5 ,-1,0
       0      .1       0   451.2     .06       0  522.85    .045       0
  550.56     .06       0  673.82      .1       0
#XS Ineff= 2 , 0
          403.65  2256.9
Permanent Ineff=
       F       F
Bank Sta=522.85,550.56
XS Rating Curve= 0 ,0
Exp/Cntr=0.3,0.1

Type RM Length L Ch R = 1 ,12928   ,669.9,659.9,642.7
XS GIS Cut Line= 4
2299800.24703648655114.3856376282300223.51335391655216.883284576
2300410.73392248655332.685332278 2300800.5006509655435.572535074
#Sta/Elev= 30
       0 2367.41    61.7 2343.04   164.6 2297.54   189.2 2283.53   201.6 2280.15
   213.9 2271.43   283.9  2234.5   333.3 2236.27   366.7 2233.46   465.3 2236.61
     474 2234.74  480.262230.765     488 2228.94  512.482230.765   526.3 2234.84
   563.3 2237.19   586.8 2234.15     615 2236.82   657.2  2235.1     703 2240.19
   722.7 2246.12   739.9 2247.41   756.4 2246.43     783  2240.5   830.7 2241.36
   847.1 2243.78   872.3 2251.71   935.4 2255.61  1012.9 2268.68  1058.8 2273.61
#Mann= 5 ,-1,0
       0      .1       0  480.26    .045       0  512.48      .1       0
   585.5     .06       0   655.5      .1       0
#XS Ineff= 2 , 0
           462.2 2259.59
Permanent Ineff=
       F       F
Bank Sta=480.26,512.48
XS Rating Curve= 0 ,0
Exp/Cntr=0.3,0.1

Type RM Length L Ch R = 1 ,12268   ,589.8,580.9,566.4
XS GIS Cut Line= 4
2299781.59275395655950.0848330012300171.03681719655844.325817192
2300546.70332463655735.3829092642300864.80973123655588.353697622
#Sta/Elev= 30
       0 2390.03    51.7 2370.41      69 2362.31   118.7 2347.35   168.5 2327.26
   222.4    2309   250.6  2297.8   259.7 2292.66   267.9 2292.09   313.5 2274.96
   363.3 2259.83     384 2251.89   400.6  2243.5   425.6 2222.98  430.882220.156
     449 2218.81  463.022220.156   475.5 2224.57   479.7 2224.75   636.2 2223.17
   646.3 2225.71   654.6 2232.28   658.8 2234.41     663 2234.74   813.9 2239.34
   937.3 2238.08   968.2 2243.17  1029.9 2250.16  1091.6 2265.62  1145.1 2272.85
#Mann= 7 ,-1,0
       0      .1       0  430.88    .045       0  463.02      .1       0
  483.55     .06       0  583.55      .1       0  793.55     .06       0
  834.69     .05       0
#XS Ineff= 2 , 0
                          606.71         2231.69
Permanent Ineff=
       F       F
Bank Sta=430.88,463.02
XS Rating Curve= 0 ,0
Exp/Cntr=0.3,0.1

Type RM Length L Ch R = 1 ,11687   ,327.6,322.7,319.2
XS GIS Cut Line= 4
2300232.99681719656559.2408488112300491.62755533656347.652758403
2300631.85358647656141.3894768682300877.40938143655765.465765312
#Sta/Elev= 30
       0 2376.45   102.3 2339.66   225.4 2294.07     234 2289.92   265.2 2271.37
   356.5 2232.45   363.6 2227.79   375.8 2216.56   379.5 2214.68     400  2215.4
  416.872211.732   428.5 2209.74   443.6 2209.67  452.442211.732   477.4 2214.56
   497.6 2214.32   511.3 2217.07   541.5 2216.19   564.5 2218.41   613.4 2220.43
   650.7 2220.36   679.2 2219.06   765.4 2220.39   781.6 2222.87   803.6 2228.19
   867.2 2230.75   896.1 2232.85   922.1  2236.6   975.6 2247.65  1032.6 2262.59
#Mann= 6 ,-1,0
       0      .1       0  416.87    .045       0  452.44     .06       0
  603.57     .05       0  623.57     .06       0  733.57     .05       0
#XS Ineff= 2 , 0
          390.91 2236.28  484.78         2233.79
Permanent Ineff=
       F       F
Bank Sta=416.87,452.44
XS Rating Curve= 0 ,0
Exp/Cntr=0.3,0.1

Type RM Length L Ch R = 1 ,11365   ,104.1,102.9,106.1
XS GIS Cut Line= 3
2300543.46362238656728.5393872562300821.98016338656450.022846248
2301013.60906553655895.370247489
#Sta/Elev= 30
       0 2329.21    27.4  2320.9    73.6 2304.57   135.8 2276.67   157.5 2272.89
   180.1 2265.31   208.4 2258.54   282.9 2256.88   298.9 2254.68   333.8 2240.12
   349.8  2228.9     363 2227.69   378.1  2216.8   384.7 2213.95   427.7 2210.95
  436.56 2205.75     454 2204.46   461.8 2205.76     471 2207.82   504.8 2209.84
   550.4 2209.64   556.7 2211.24   576.8 2212.43   585.2 2216.48   606.4 2212.42
   644.5 2212.82   789.4 2227.32   856.1  2229.3   898.4 2235.95   980.7 2257.39
#Mann= 7 ,-1,0
       0      .1       0     180     .05       0     280      .1       0
  436.56    .045       0   461.8     .06       0  543.88     .05       0
  743.88      .1       0
#XS Ineff= 2 , 0
                          506.24         2217.77
Permanent Ineff=
       F       F
Bank Sta=436.56,461.8
XS Rating Curve= 0 ,0
Exp/Cntr(USF)=0,0
Exp/Cntr=0.3,0.1

Type RM Length L Ch R = 1 ,11262   ,53,53,53.3
XS GIS Cut Line= 6
2300585.06545789656758.9984504022300849.60985513656498.983867898
2300891.43406532656481.6423862152300928.87808425656443.804219718
 2301024.1021832656203.7138471222301103.48008576655900.942512826
#Sta/Elev= 30
       0 2324.31     139 2275.79   232.6 2259.15   314.6 2252.46   322.2 2247.98
   331.6 2237.13     345 2230.84   351.4  2224.1   356.4 2221.47   403.8  2213.2
   430.2  2210.5     482 2207.86   486.6 2207.27  493.062204.218     516 2202.35
   521.52204.229   529.8 2207.25   594.8 2211.49   628.3 2210.18   731.2 2214.12
   789.1 2227.99   809.8 2226.56   917.3  2226.9   929.7 2229.32   946.2 2236.77
   958.7 2238.66   975.2 2243.48  1004.1 2254.07  1024.8  2258.9  1041.6 2260.76
#Mann= 5 ,-1,0
       0      .1       0  490.21     .05       0  493.06    .045       0
   521.5     .06       0  719.82      .1       0
Bank Sta=493.06,521.5
XS Rating Curve= 0 ,0
Exp/Cntr=0.3,0.1

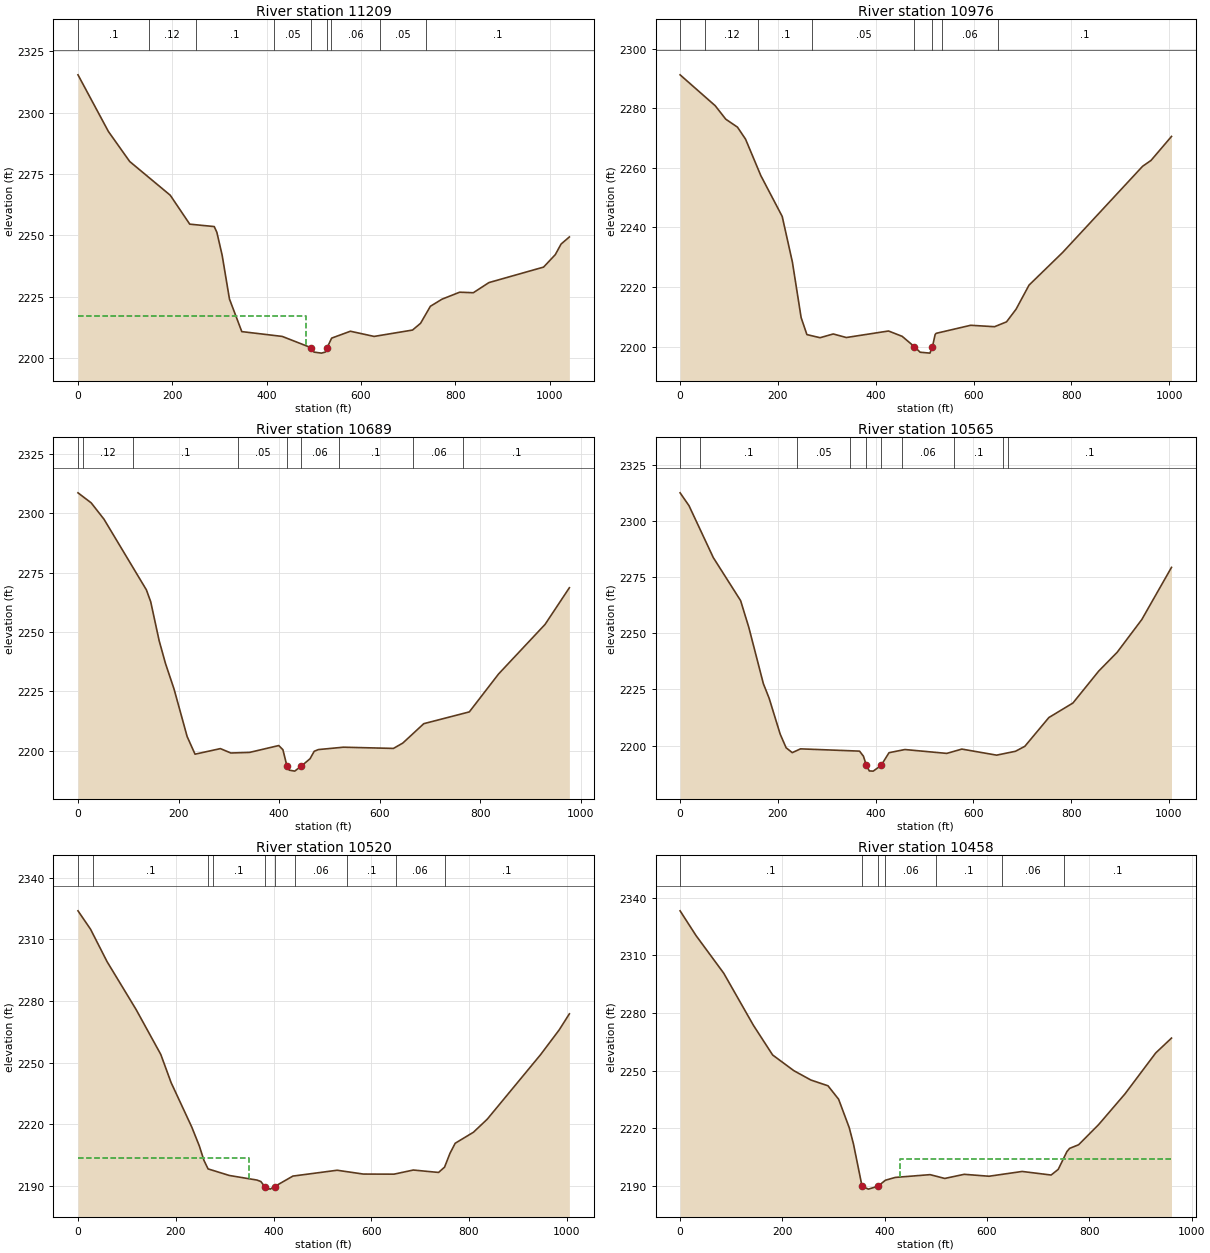
Type RM Length L Ch R = 1 ,11209   ,229.1,232.5,237.3
XS GIS Cut Line= 6
2300634.23415237656778.2802913742300898.77854961 656518.26570887
 2300940.6027598656500.9242271872300978.04677873 656463.08606069
2301073.27087768656222.9956880942301152.64878024655920.224353798
#Sta/Elev= 30
       0 2315.37    64.4 2292.33   109.6 2280.09   195.6 2266.35   236.9 2254.58
   288.8  2253.6   294.4 2251.26   305.6 2241.93   321.1  2224.1   347.2 2210.84
     433 2208.88   494.6 2204.25   500.2  2202.5   516.1 2202.08   524.7 2202.54
  527.88 2204.24   537.7 2208.19   577.4 2210.99   627.7 2208.88   709.1 2211.47
   726.1 2214.21     747 2221.16   771.6 2224.04     809 2226.88     838 2226.67
   871.1  2230.8   986.9  2237.1  1011.7 2242.16    1024 2246.48  1041.6 2249.38
#Mann= 9 ,-1,0
       0      .1       0     150     .12       0     250      .1       0
  416.34     .05       0   494.6    .045       0  527.88     .05       0
  537.21     .06       0  639.82     .05       0  738.59      .1       0
#XS Ineff= 2 , 0
          483.16 2217.11
Permanent Ineff=
       F       F
Bank Sta=494.6,527.88
XS Rating Curve= 0 ,0
Exp/Cntr=0.3,0.1

Type RM Length L Ch R = 1 ,10976   ,276.4,287.1,299.9
XS GIS Cut Line= 4
2300792.74771214656798.0208224062301136.83523112656624.440957918
2301259.72363076656449.3249884342301413.33413031656074.515369539
#Sta/Elev= 30
       0 2291.23    71.7 2280.87    93.4 2276.33   117.3 2273.66   133.8 2269.63
   165.1 2257.36   208.7 2243.69   229.5 2228.39   247.4 2209.72   259.2 2204.01
   286.1 2202.97     313 2204.22   339.8 2203.03     426 2205.22   453.9 2203.43
   479.1 2199.93   490.6 2198.09   510.7 2197.79  515.762199.914   521.3 2204.03
   523.5 2204.44     594 2207.14   642.7 2206.66   667.2 2208.29   686.7 2212.53
   713.2 2220.62   781.9 2231.59   945.3 2260.52   962.6  2262.5  1004.4 2270.54
#Mann= 8 ,-1,0
       0      .1       0      50     .12       0     160      .1       0
     270     .05       0   479.1    .045       0  515.76     .05       0
  535.39     .06       0  649.32      .1       0
Bank Sta=479.1,515.76
XS Rating Curve= 0 ,0
Exp/Cntr(USF)=0,0
Exp/Cntr=0.3,0.1

Type RM Length L Ch R = 1 ,10689   ,120.8,123.8,126.5
XS GIS Cut Line= 4
2300931.33138432656903.6057372472301167.26056398656823.603825954
2301550.82580832 656719.016374232301755.17139607656459.170058793
#Sta/Elev= 30
       0  2308.6    26.2 2304.39    51.6 2297.53     136 2267.78   144.6 2262.79
   161.4 2246.38   174.1 2236.72     191 2226.04   217.1 2206.01   232.8 2198.59
   283.2 2200.94     304 2199.09   341.3 2199.34   399.3 2202.23   407.6 2200.46
  415.532193.632   420.1 2191.87     431 2191.46  444.442193.632   461.5 2196.67
   469.8 2199.81   478.1 2200.53   527.9 2201.53   627.4 2201.02     646 2203.27
   687.7 2211.43   778.3 2216.39   836.5 2232.36   928.9 2253.21   977.3 2268.65
#Mann= 9 ,-1,0
       0     .05       0      10     .12       0     110      .1       0
  319.12     .05       0  415.53    .045       0  444.44     .06       0
  519.12      .1       0  666.69     .06       0  766.69      .1       0
Bank Sta=415.53,444.44
XS Rating Curve= 0 ,0
Exp/Cntr=0.3,0.1

Type RM Length L Ch R = 1 ,10565   ,45.8,45.8,45.9
XS GIS Cut Line= 6
2301002.92493194656943.0823236242301254.88455382656857.416052184
2301342.69941194656894.6993946562301479.60048284656876.863691758
2301668.55235041656785.6707833252301869.57349797656569.478228407
#Sta/Elev= 30
       0 2312.47    18.2 2306.76      68 2283.62   123.8  2264.5   140.7  2252.5
   170.3 2227.58   182.2 2221.02   204.7 2205.12   216.9 2199.01   229.5 2196.84
   246.4 2198.52   367.1 2197.51   375.1 2195.25  380.922191.267   387.1  2188.7
   395.1 2188.61   411.3 2191.16   427.4 2196.81   459.9 2198.22   545.6  2196.5
   576.4 2198.42   647.5 2195.72   686.2 2197.45   705.3 2199.66   754.5 2212.47
   803.6 2218.91   856.4 2233.13   894.2 2241.51   944.5 2256.06  1005.3 2279.29
#Mann= 10 ,-1,0
       0     .05       0      40      .1       0     240     .05       0
  348.14      .1       0  380.92    .045       0   411.3      .1       0
  454.29     .06       0   560.3      .1       0   660.3     .06       0
   670.3      .1       0
Bank Sta=380.92,411.3
XS Rating Curve= 0 ,0
Exp/Cntr(USF)=0,0
Exp/Cntr=0.3,0.1

Type RM Length L Ch R = 1 ,10520   ,64.7,62,62.1
XS GIS Cut Line= 6
2301011.85171016656987.7162147612301263.81133205656902.049943321
2301351.62619017656939.3332857942301488.52726107656921.497582895
2301677.47912864656830.304674463 2301878.5002762656614.112119544
#Sta/Elev= 30
       0 2323.83    25.7 2314.89    59.5 2299.12   118.9 2275.84   169.4    2254
   190.5  2240.3   232.7 2218.73   248.2 2209.52   257.6 2202.54   266.1 2198.34
   309.6 2195.14   366.1 2192.91   374.1 2192.21   382.1  2189.7   393.3  2188.5
   402.3 2189.75   439.6 2194.84   530.2 2197.68   583.9 2195.82   646.5 2195.78
     686 2197.78   737.6 2196.61   749.9 2199.17   760.9 2205.85   771.7 2210.81
     809 2216.16   837.3 2222.52   946.5 2253.93   984.3 2265.88  1005.3 2273.74
#Mann= 10 ,-1,0
       0     .05       0      30      .1       0  266.12     .05       0
  276.12      .1       0   382.1    .045       0   402.3      .1       0
  444.29     .06       0   550.3      .1       0   650.3     .06       0
  750.11      .1       0
#XS Ineff= 2 , 0
          350.32 2203.79
Permanent Ineff=
       F       F
Bank Sta=382.1,402.3
XS Rating Curve= 0 ,0
Exp/Cntr(USF)=0,0
Exp/Cntr=0.3,0.1

Type RM Length L Ch R = 1 ,10458   ,78.1,73.7,69.6
XS GIS Cut Line= 3
2301050.17529839657099.3353018352301521.51098317656964.837997844
2301886.91516304656668.467832413
#Sta/Elev= 30
       0 2333.23    31.2 2320.33    85.3 2300.75   143.5 2273.55   180.9 2258.18
   222.5 2249.98   255.8 2245.12   289.1 2242.14   309.9 2235.13   330.7 2220.28
     339 2211.74   355.7 2189.81   368.1 2188.33  386.66 2189.82   401.4 2192.97
   420.8 2194.43   488.7 2195.87   517.4 2193.89   555.4 2196.04   603.9 2195.04
   668.7 2197.53   725.3 2195.67   739.2 2198.62   756.2 2207.89   761.4 2209.54
     779 2211.43     818 2221.88   869.6 2237.89   929.7 2259.21   960.6 2266.97
#Mann= 7 ,-1,0
       0      .1       0   355.7    .045       0  386.66      .1       0
     400     .06       0  500.15      .1       0  630.15     .06       0
  750.15      .1       0
#XS Ineff= 2 , 0
                          429.92         2204.18
Permanent Ineff=
       F       F
Bank Sta=355.7,386.66
XS Rating Curve= 0 ,0
Exp/Cntr(USF)=0,0
Exp/Cntr=0.3,0.1