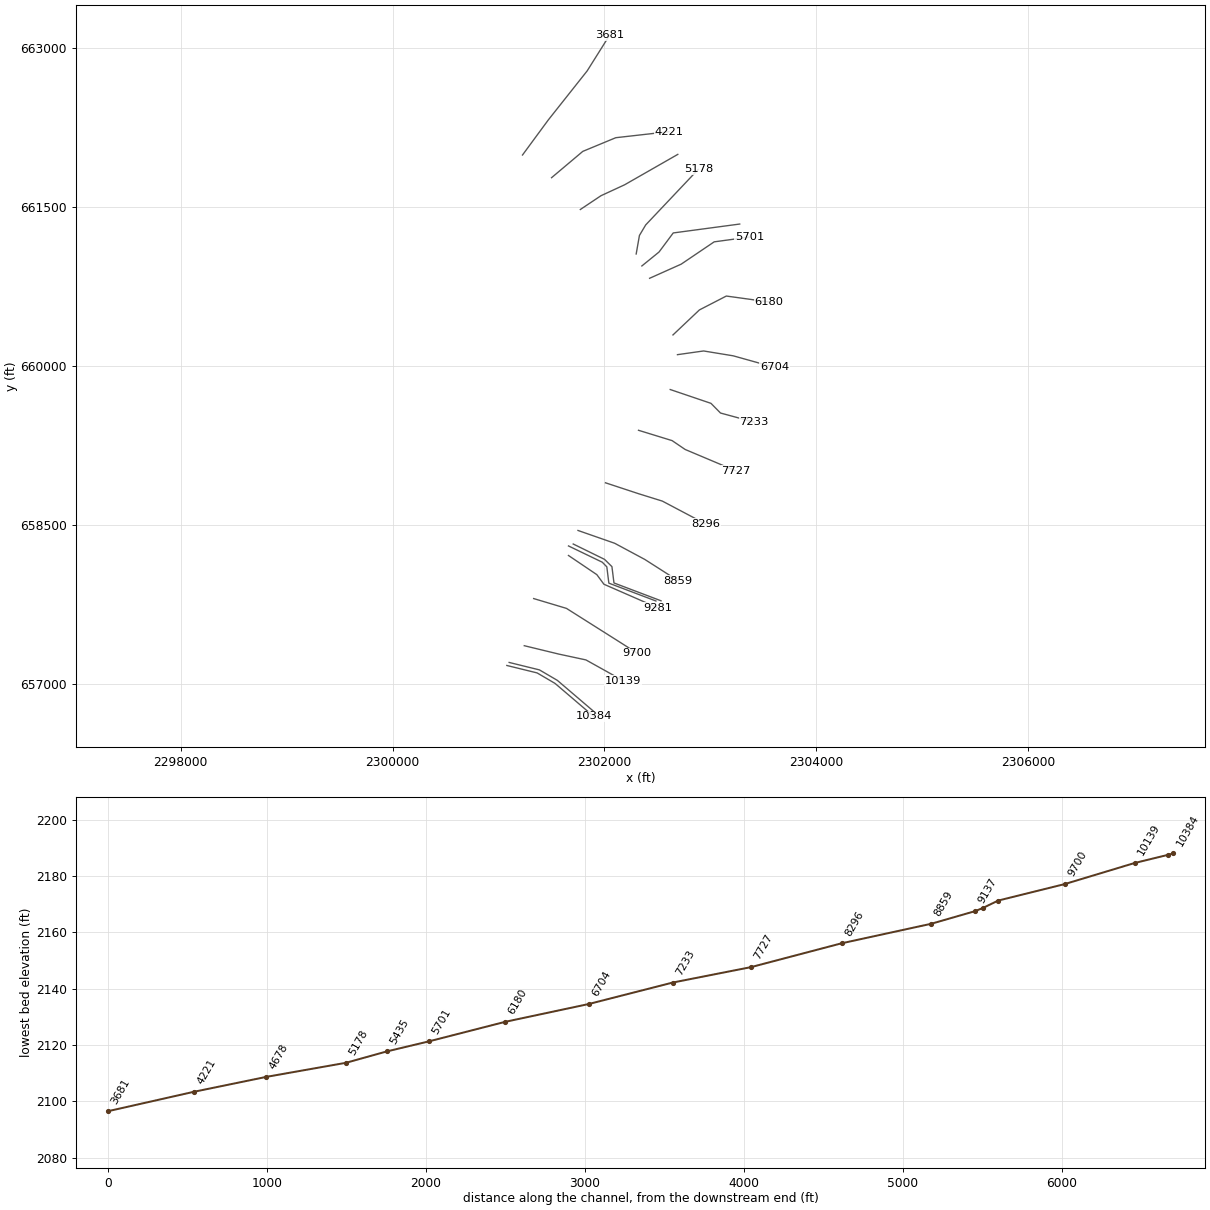
HEC-RAS study RFFILESCK.prj: RFFILESCK

--- RFFILESCK.g01 (geometry) --- (continued)

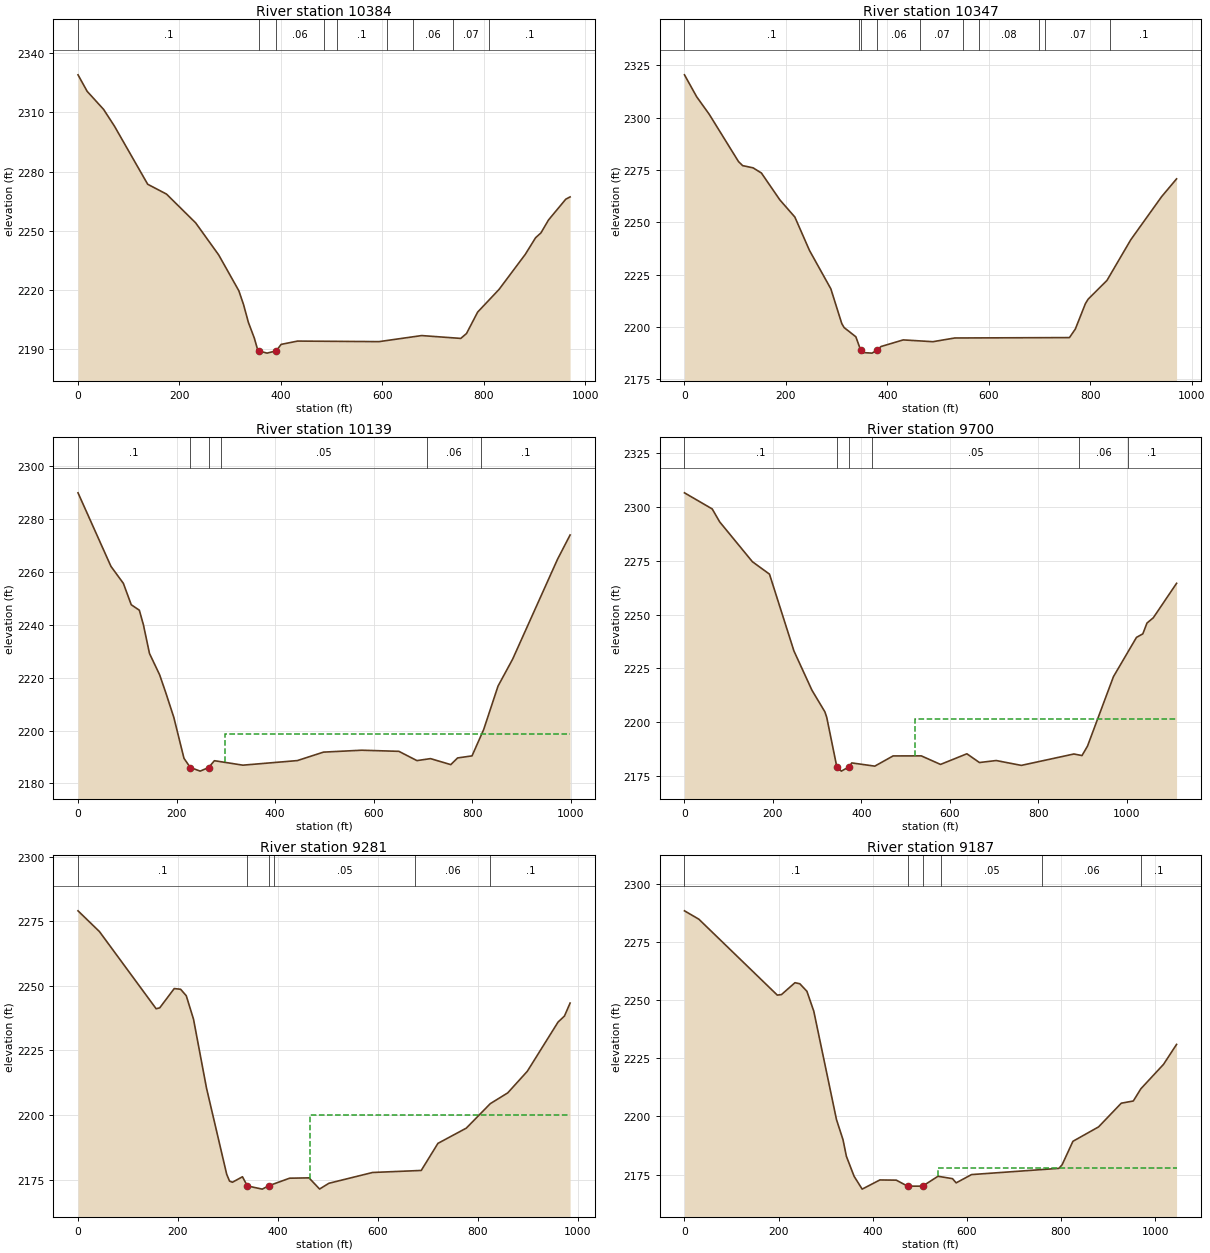
Type RM Length L Ch R = 1 ,10384   ,36.1,37,36.3
XS GIS Cut Line= 4
2301078.74109747657176.7010076712301364.39908824657106.476751605
2301533.41339946657007.6866964612301898.81757932656695.843389862
#Sta/Elev= 30
       0 2328.99      18 2320.64    50.4 2311.49    71.5 2303.15   137.4 2273.58
   174.5  2268.6     232 2254.02   277.5 2237.75   317.1 2219.66   326.3 2212.73
   335.9 2203.67   347.6 2195.71   354.1  2189.9   356.4 2189.22   372.7 2188.07
  390.85 2189.22   400.5 2192.49   432.9 2194.17   593.5 2193.89   677.6 2196.96
   754.7 2195.52     766 2197.99     788 2208.85   830.1  2220.3     882 2238.11
   902.2 2246.49   912.8 2248.95   927.8 2255.52   961.8 2266.03   970.3 2267.17
#Mann= 9 ,-1,0
       0      .1       0   356.4    .045       0  390.85     .06       0
  484.16     .07       0  509.93      .1       0  609.93     .08       0
  659.93     .06       0  739.93     .07       0  809.93      .1       0
Bank Sta=356.4,390.85
XS Rating Curve= 0 ,0
Exp/Cntr(USF)=0,0
Exp/Cntr=0.3,0.1

Type RM Length L Ch R = 1 ,10347   ,204.2,207.9,213.3
XS GIS Cut Line= 4
2301100.76056759657205.2668067482301386.41855837657135.042550682
2301555.43286958657036.2524955392301920.83704945 656724.40918894
#Sta/Elev= 30
       0 2320.39    24.1 2309.89    48.8 2301.55   106.5 2278.98   114.7 2277.04
   135.3 2275.98   151.7 2273.51     188  2260.7   217.6  2252.5   246.5 2236.54
   288.6 2218.22   310.1 2201.66   314.7 2199.74   337.9 2195.33   347.2 2189.07
   352.4 2187.77   369.9 2187.52  380.18 2189.06   387.5 2190.67   431.3 2193.83
   489.9 2192.98     533 2194.75   759.1 2194.94   770.7 2199.03   790.6 2211.18
   795.9 2213.27   833.1 2222.25     880 2241.65   940.9 2262.25   970.3 2270.72
#Mann= 10 ,-1,0
       0      .1       0  344.16     .06       0   347.2    .045       0
  380.18     .06       0  464.16     .07       0  549.93      .1       0
  579.93     .08       0  699.93     .06       0  709.93     .07       0
  839.93      .1       0
Bank Sta=347.2,380.18
XS Rating Curve= 0 ,0
Exp/Cntr(USF)=0,0
Exp/Cntr=0.3,0.1

Type RM Length L Ch R = 1 ,10139   ,444.7,439,433.6
XS GIS Cut Line= 4
2301243.26219727 657363.342623022301569.20510124657284.210300236
2301825.22087282657229.2061077542302175.68913404657034.004011356
#Sta/Elev= 30
       0 2289.82    66.8 2262.04      92 2255.61     108 2247.53   124.4 2245.46
   132.7 2239.94     145 2229.12   165.6 2221.05   178.1 2214.27   194.4 2204.94
     215 2189.48   227.8 2186.02   247.9 2184.65  264.94 2186.01   276.7 2188.59
   334.4  2186.9   444.9 2188.63     498 2191.83   575.7 2192.55     651 2192.13
   687.7 2188.62   715.1 2189.38   756.3 2187.11   770.1 2189.63   799.4 2190.41
     823 2200.34   852.2  2216.8   881.8 2226.96   972.9 2264.72   998.4 2273.89
#Mann= 6 ,-1,0
       0      .1       0   227.8    .045       0  264.94      .1       0
     290     .05       0  707.27     .06       0  817.27      .1       0
#XS Ineff= 2 , 0
                          297.94          2198.5
Permanent Ineff=
       F       F
Bank Sta=227.8,264.94
XS Rating Curve= 0 ,0
Exp/Cntr=0.3,0.1

Type RM Length L Ch R = 1 ,9700    ,422.3,418.5,408.9
XS GIS Cut Line= 4
2301332.06946048657808.2051897172301641.48268284657715.527275318
2302122.75677625657411.2730258622302308.59517495657293.124881143
#Sta/Elev= 30
       0 2306.67    62.7 2299.17    79.6 2293.15   153.5 2274.62   192.2 2268.83
   247.5 2233.07   288.2 2214.82   317.5 2204.74   321.6 2202.25  344.412179.199
   354.6 2177.17  372.442179.198   378.2 2180.99   430.3 2179.49   471.6 2184.24
   535.4 2184.27   578.9 2180.29   638.5 2185.24   666.9 2181.17   704.8  2182.1
   761.6 2179.84   880.4 2185.14   898.8 2184.41   911.2  2188.8   969.9 2221.14
    1022 2239.41  1036.3 2241.05  1045.7 2246.07    1060 2248.53  1112.6 2264.56
#Mann= 6 ,-1,0
       0      .1       0  344.41    .045       0  372.44      .1       0
  422.99     .05       0  892.38     .06       0 1002.38      .1       0
#XS Ineff= 2 , 0
                          521.77         2201.52
Permanent Ineff=
       F       F
Bank Sta=344.41,372.44
XS Rating Curve= 0 ,0
Exp/Cntr=0.3,0.1

Type RM Length L Ch R = 1 ,9281    ,98.2,94.7,78
XS GIS Cut Line= 4
2301660.60871807658214.7805118182301928.41308442658033.863784326
 2301995.0666156 657943.405420582302498.53882435657723.210719356
#Sta/Elev= 30
       0 2279.03    42.9    2271   156.4 2241.13   163.6 2241.48   192.6 2248.94
   205.4 2248.67   216.7 2246.17   231.2  2237.1   257.2 2210.44   297.6 2177.09
   303.3 2174.43   309.1 2173.97   329.2  2176.1   338.9 2172.56   368.8 2171.31
  381.49 2172.59   423.6 2175.54   462.4 2175.67   483.6 2171.35   502.2 2173.57
   589.6 2177.75   687.1 2178.54   720.5 2189.02   777.3 2194.92   825.3 2204.39
   860.3 2208.57   899.5 2216.94     961 2235.97   973.8 2238.31   985.1 2243.32
#Mann= 6 ,-1,0
       0      .1       0   338.9    .045       0  381.49      .1       0
  393.19     .05       0  675.55     .06       0  825.55      .1       0
#XS Ineff= 2 , 0
                          464.68         2199.95
Permanent Ineff=
       F       F
Bank Sta=338.9,381.49
XS Rating Curve= 0 ,0
Exp/Cntr(USF)=0,0
Exp/Cntr=0.3,0.1

Type RM Length L Ch R = 1 ,9187    ,53.1,50,52.1
XS GIS Cut Line= 5
2301660.71568216658304.9097635542301979.77786052658151.215732286
2302022.53806955658107.7324521562302041.71731626 657953.73602538
2302486.02365851657785.393675371
#Sta/Elev= 30
       0 2288.29    30.5  2284.7   197.2 2252.08   206.1 2252.31   234.7 2257.41
   245.1 2256.96   260.1 2253.72   274.7 2245.19     323 2198.55   336.8 2189.96
     344 2182.82   360.4 2174.23   377.5 2168.72   415.1 2172.66     450 2172.58
   474.1 2169.99  505.96    2170   538.6 2174.24   569.4 2173.22   577.2 2171.41
   609.9 2174.97   795.4 2177.64   802.2 2179.14   825.3 2189.27   879.8 2195.46
     928 2205.64   953.6 2206.59   969.7 2211.85  1017.8 2222.33  1045.5  2230.9
#Mann= 6 ,-1,0
       0      .1       0   474.1    .045       0  505.96      .1       0
  545.14     .05       0  760.32     .06       0  970.32      .1       0
#XS Ineff= 2 , 0
                          539.47            2178
Permanent Ineff=
       F       F
Bank Sta=474.1,505.96
XS Rating Curve= 0 ,0
Exp/Cntr=0.3,0.1

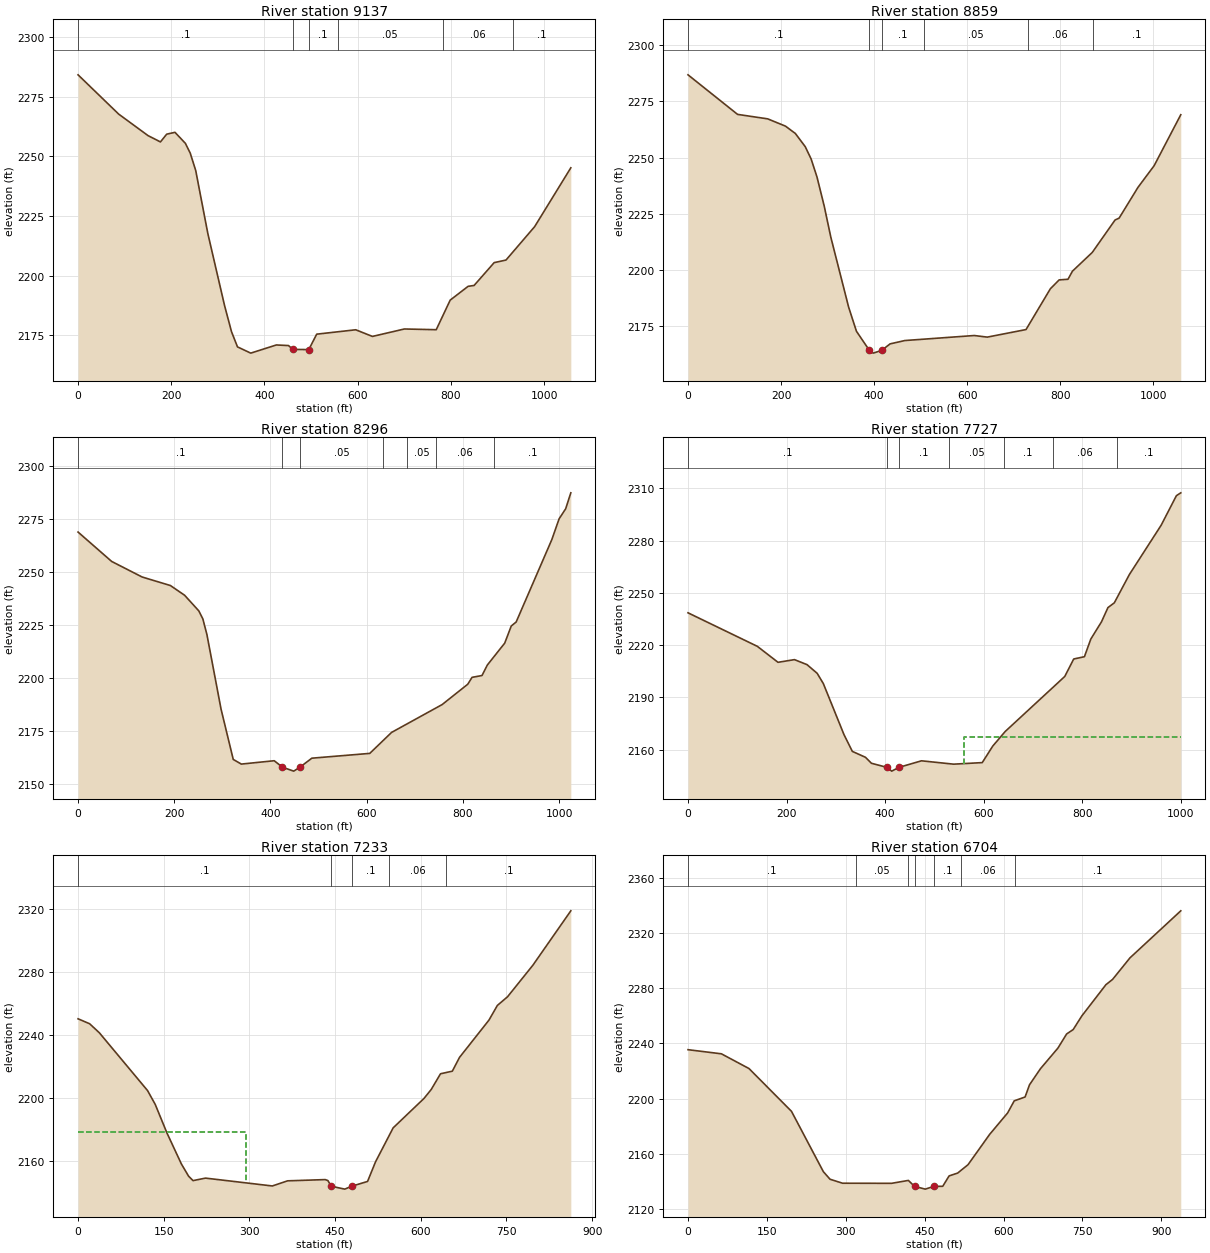
Type RM Length L Ch R = 1 ,9137    ,260.1,277.1,291.3
XS GIS Cut Line= 5
2301705.45306225658323.1873569922302001.08771465658178.170187193
2302070.74619423658109.5240088012302089.92544094657955.527582024
2302534.23178319657787.185232016
#Sta/Elev= 30
       0 2284.24    87.2 2267.77   150.2 2258.75   176.8 2256.11   190.2 2259.36
     208 2260.13   230.3 2255.52   240.7 2251.43   252.5 2244.12   278.5  2217.7
   314.4 2187.49   329.3 2176.54   342.1 2170.18   370.6 2167.56   425.5 2170.98
   451.6 2170.73     461 2169.13   495.12169.035   512.1 2175.51   595.9 2177.35
   631.7 2174.56   700.2 2177.68   768.6 2177.38   798.6 2189.79     837 2195.56
   849.9 2195.94   892.9  2205.5   918.3 2206.58   979.8 2220.59  1057.4 2245.26
#Mann= 6 ,-1,0
       0      .1       0     461    .045       0   495.1      .1       0
  557.09     .05       0  782.27     .06       0  932.27      .1       0
Bank Sta=461,495.1
XS Rating Curve= 0 ,0
Exp/Cntr=0.3,0.1

Type RM Length L Ch R = 1 ,8859    ,556.8,563.8,566.8
XS GIS Cut Line= 4
2301750.37441544658451.0228859182302096.44566099658330.235085797
2302381.21304213658177.3420535952302692.52731653657978.519764997
#Sta/Elev= 30
       0 2286.83   106.5 2269.24   171.4 2267.24   209.5 2264.01   230.7 2260.75
   251.9 2254.91   264.6 2249.42   277.3 2241.34   292.8 2228.41   306.9 2214.67
   345.2 2183.54     362 2172.79  389.89 2164.27     398 2163.06   416.2 2164.27
   434.3 2167.17   466.1 2168.66   615.3 2170.89   643.2 2170.18   726.5 2173.54
   778.9 2191.71   797.7 2195.62   816.7 2195.91   826.2 2199.49   868.9 2207.85
   917.9 2222.27   926.6 2223.11   967.2 2236.81  1001.8  2246.4  1059.1 2269.08
#Mann= 6 ,-1,0
       0      .1       0  389.89    .045       0   416.2      .1       0
  506.54     .05       0  729.76     .06       0  869.76      .1       0
Bank Sta=389.89,416.2
XS Rating Curve= 0 ,0
Exp/Cntr=0.3,0.1

Type RM Length L Ch R = 1 ,8296    ,574.3,568.6,564.4
XS GIS Cut Line= 4
 2302009.7849179658900.9033443942302324.38532204658797.201558822
2302546.94407356658728.0133050952302953.62720001658513.178502491
#Sta/Elev= 30
       0 2268.78    69.9 2254.93   133.1 2247.61     192 2243.58   221.5    2239
     251 2231.65   259.4 2227.87   267.9 2220.44   297.3 2185.29   322.6 2161.63
   339.4 2159.44   407.8 2161.02  424.91 2157.96   448.3 2156.12   460.9 2157.92
     486 2162.22   606.4 2164.48   651.7 2174.36   756.8 2187.48   810.1 2197.08
     819 2200.31   839.7 2201.18   850.7  2206.1   886.9 2216.44   900.5 2224.51
   910.7  2226.4   984.7 2265.16    1000 2275.04  1013.6 2279.75  1024.3 2287.27
#Mann= 7 ,-1,0
       0      .1       0  424.91    .045       0   460.9     .05       0
  634.32     .06       0  684.32     .05       0  744.32     .06       0
  864.32      .1       0
Bank Sta=424.91,460.9
XS Rating Curve= 0 ,0
Exp/Cntr=0.3,0.1

Type RM Length L Ch R = 1 ,7727    ,496.1,493.7,490.8
XS GIS Cut Line= 4
 2302321.6760527659396.472697622 2302638.8771054659298.983631534
2302761.60058284659215.5850045882303240.35904579659013.696888121
#Sta/Elev= 30
       0 2238.55   140.7  2219.3   182.6 2210.14     216 2211.67   241.5  2208.8
   262.1 2203.81   274.6 2197.91   316.5 2168.62   333.4    2159     360 2155.62
   372.1 2152.19   403.2 2149.86   413.3 2147.67  428.31 2149.86   473.7 2153.59
     539 2151.67     597 2152.56   618.4 2162.08   643.6 2170.43   764.4 2202.01
   782.6 2212.04   804.3 2213.35   817.3  2223.5     839 2233.42     852 2241.53
     865  2244.3   895.4 2260.47     960 2288.83   990.9 2305.79   999.8 2307.43
#Mann= 7 ,-1,0
       0      .1       0   403.2    .045       0  428.31      .1       0
  530.22     .05       0  640.22      .1       0  740.22     .06       0
  870.22      .1       0
#XS Ineff= 2 , 0
                          559.26         2167.43
Permanent Ineff=
       F       F
Bank Sta=403.2,428.31
XS Rating Curve= 0 ,0
Exp/Cntr=0.3,0.1

Type RM Length L Ch R = 1 ,7233    ,516.3,529.3,539.1
XS GIS Cut Line= 4
 2302620.9249165659781.2156185732303005.51507905659650.772099309
2303095.58034467659559.3794704112303412.30132955659473.427532616
#Sta/Elev= 30
       0 2250.14    20.3 2246.99    37.3 2241.27   121.7 2204.63   135.1 2195.87
   155.5 2177.87   180.8 2158.18   193.5 2150.38   201.3 2147.56   223.1 2149.15
   340.1 2144.17   366.7 2147.42   432.7 2148.21   437.4 2147.58  443.242144.011
   466.9 2142.17  479.082144.009   506.8 2147.04   520.7 2159.44   551.6 2181.01
   605.5 2199.62   618.2 2205.31   634.5 2215.29   655.2 2216.94   667.7 2225.65
   719.3  2249.3     734  2258.6   751.9 2264.13   796.2 2284.11   862.6 2318.58
#Mann= 5 ,-1,0
       0      .1       0  443.24    .045       0  479.08      .1       0
  544.42     .06       0  644.42      .1       0
#XS Ineff= 2 , 0
          293.66 2178.35
Permanent Ineff=
       F       F
Bank Sta=443.24,479.08
XS Rating Curve= 0 ,0
Exp/Cntr=0.3,0.1

Type RM Length L Ch R = 1 ,6704    ,510.4,524.2,533.3
XS GIS Cut Line= 4
2302689.33865788660110.3136250542302935.89139202660145.167135018
2303215.68206566660099.3166842332303605.20723024659990.465019869
#Sta/Elev= 30
       0 2235.43    63.5 2232.45     116 2221.78   196.8 2190.81   257.4 2147.14
   270.1 2141.68   293.9  2138.8   387.1 2138.73     419 2140.83  430.892136.498
   451.2 2134.53  467.072136.496   484.4 2136.59   496.5  2144.1   512.8 2146.16
   532.5 2152.22   573.6 2174.16   607.8 2189.68   620.3  2198.4     641 2201.22
   649.3    2210   670.1 2221.62   703.5 2236.63   719.9 2246.79   732.4 2249.99
   748.9 2259.89   794.7 2282.49   807.2 2286.24   840.4 2301.88     937 2335.92
#Mann= 7 ,-1,0
       0      .1       0     319     .05       0     419      .1       0
  430.89    .045       0  467.07      .1       0     519     .06       0
  622.53      .1       0
Bank Sta=430.89,467.07
XS Rating Curve= 0 ,0
Exp/Cntr=0.3,0.1

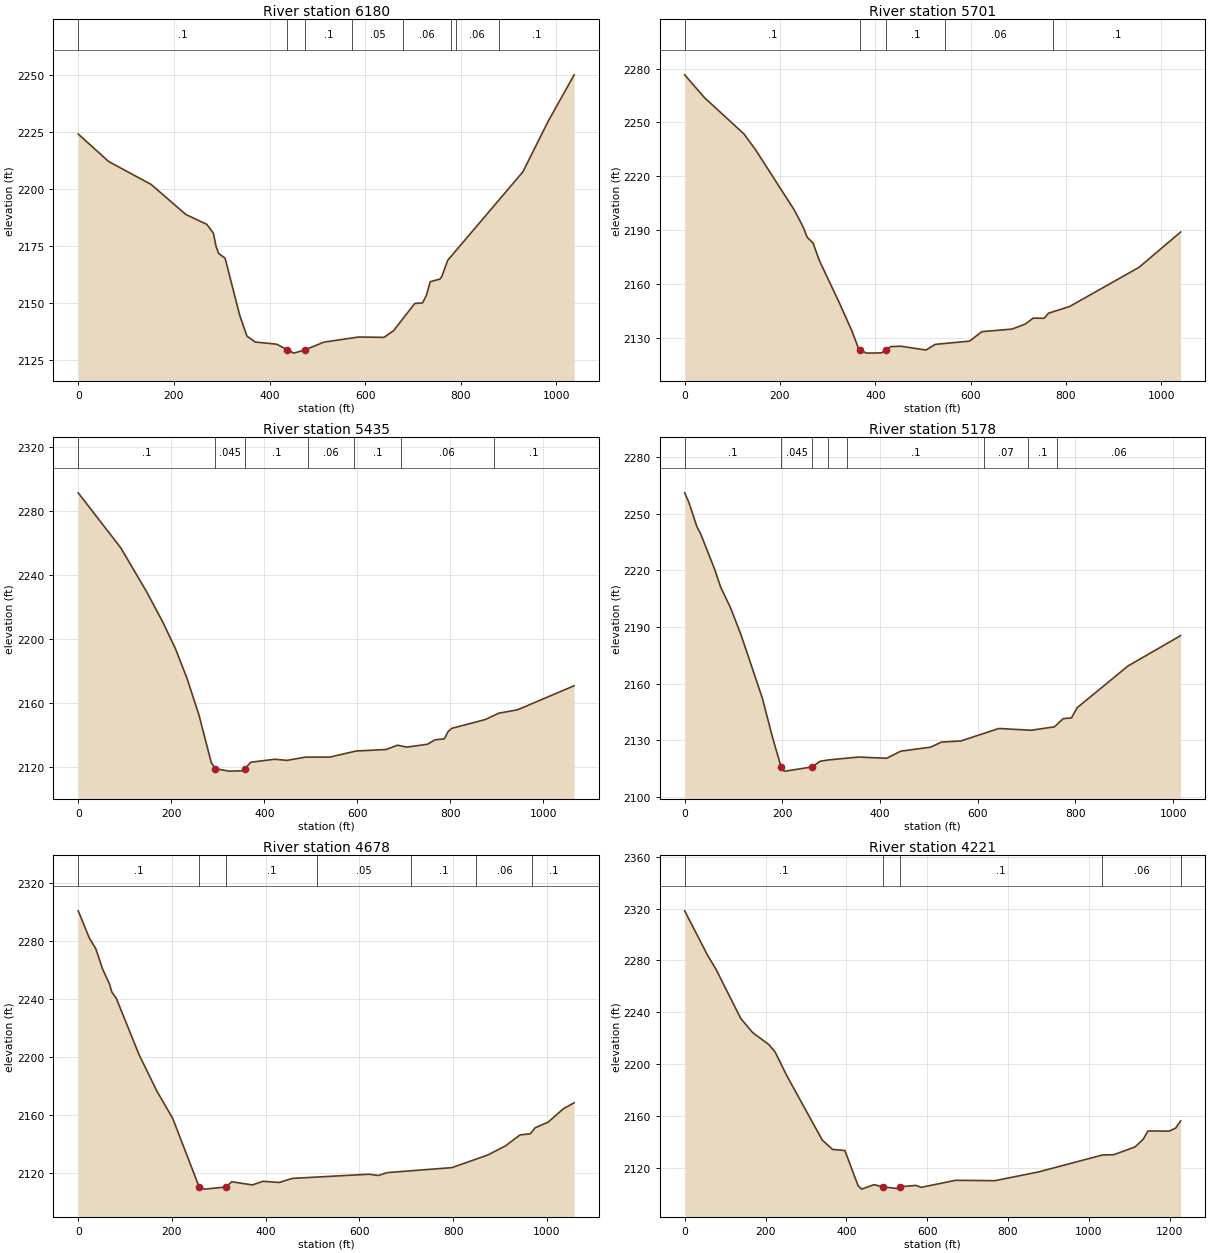
Type RM Length L Ch R = 1 ,6180    ,471.8,478.7,479.8
XS GIS Cut Line= 4
      2302646.84      660296.4322302896.36128321660532.484084962
2303150.44208049660663.5553032942303554.24815254660607.849594731
#Sta/Elev= 30
       0 2224.08    63.7 2212.05   152.4 2202.03     225 2188.89   268.8 2184.57
   282.7  2180.7   288.2  2174.9   293.7 2171.83   307.1 2169.79   337.7 2144.79
   352.8 2135.66   370.3 2133.08   415.1 2132.12  437.522129.648   450.8 2128.22
  474.042129.647   514.3 2133.06   586.3 2135.26   639.2 2135.12   659.4 2138.03
   703.8 2149.96     720 2150.19     728 2153.49   736.1 2159.47   756.3 2160.61
   760.3 2161.73   772.5  2168.8   929.9 2207.56   982.4 2229.55    1037 2249.98
#Mann= 8 ,-1,0
       0      .1       0  437.52    .045       0  474.04      .1       0
  573.48     .05       0  679.38     .06       0  779.38      .1       0
  789.38     .06       0  879.38      .1       0
Bank Sta=437.52,474.04
XS Rating Curve= 0 ,0
Exp/Cntr=0.3,0.1

Type RM Length L Ch R = 1 ,5701    ,251.8,266.2,270.9
XS GIS Cut Line= 4
      2302426.31  660831.11937912302724.32777559660964.467113282
2303036.04150433661175.1539880132303370.99771055661220.541136962
#Sta/Elev= 30
       0 2276.48    41.5 2263.76   124.1  2243.6   148.3 2234.87   230.3 2200.97
   248.2 2191.87   257.3 2185.83   269.4  2182.7   282.5 2172.98   323.9 2149.72
   350.4 2133.97   364.3 2124.33  367.722123.154   381.6 2121.29   413.3 2121.44
  421.762123.163   432.5 2124.94   453.7 2125.15   506.3    2123   525.7 2126.17
   597.7 2127.98   623.6 2133.26     687 2134.69     715 2137.54   731.1 2140.79
   754.4 2140.73   763.4 2143.55   807.9  2147.3   953.5 2169.15  1040.7 2188.81
#Mann= 5 ,-1,0
       0      .1       0  367.72    .045       0  421.76      .1       0
  546.49     .06       0  772.73      .1       0
Bank Sta=367.72,421.76
XS Rating Curve= 0 ,0
Exp/Cntr=0.3,0.1

Type RM Length L Ch R = 1 ,5435    ,249.2,256.9,255.8
XS GIS Cut Line= 4
 2302353.3072375660947.5370130852302515.47229414661079.265692777
2302649.40248128 661259.130675942303276.84133315661343.151969974
#Sta/Elev= 30
       0 2291.27    91.4    2257     148 2229.11   182.3  2210.4   208.9 2194.17
   233.7 2175.73   259.4 2152.93   286.1 2123.01  294.962119.271     324  2117.7
     351 2117.88  358.822119.271   370.8 2123.25   422.3 2125.11   448.6  2124.4
   488.4 2126.42   540.9 2126.45   597.4 2130.24   661.7 2131.18   686.6 2133.88
   706.4 2132.69   750.7 2134.44   766.9 2137.21   787.1 2137.82   795.2 2142.39
   803.2 2144.38   875.2 2149.86   904.1 2153.83   944.5 2155.94  1066.2 2170.95
#Mann= 7 ,-1,0
       0      .1       0  294.96    .045       0  358.82      .1       0
  493.18     .06       0  593.18      .1       0  693.18     .06       0
  893.18      .1       0
Bank Sta=294.96,358.82
XS Rating Curve= 0 ,0
Exp/Cntr=0.3,0.1

Type RM Length L Ch R = 1 ,5178    ,516.9,500.5,480.8
XS GIS Cut Line= 4
2302299.62011957661060.6055517252302330.34424594661235.496732581
2302389.42910434661334.7592946882302885.74191487661859.432837257
#Sta/Elev= 30
       0 2261.09     8.7 2255.94    24.9 2243.25    33.1 2239.14    61.5 2220.48
    73.5 2211.26      94 2200.11     115 2186.13     159 2152.32   179.5 2131.84
  197.432115.894   202.8 2113.77   206.4 2113.66  260.742115.893   277.3 2118.89
   293.9 2119.58   356.2 2121.12   413.5 2120.47   442.6 2124.25   503.3 2126.35
   525.9 2129.04   565.5 2129.65   643.3 2136.26   709.4 2135.31   756.9 2137.12
   774.9 2141.45   791.9 2141.85   803.5 2147.26   907.6 2169.37  1015.3 2185.44
#Mann= 8 ,-1,0
       0      .1       0  197.43    .045       0  260.74      .1       0
  293.09     .05       0  333.09      .1       0  613.09     .07       0
  703.09      .1       0  763.09     .06       0
Bank Sta=197.43,260.74
XS Rating Curve= 0 ,0
Exp/Cntr(USF)=0,0
Exp/Cntr=0.3,0.1

Type RM Length L Ch R = 1 ,4678    ,460.2,456.6,455
XS GIS Cut Line= 4
2301772.52763498 661480.438836372301967.35314475661610.473006294
2302189.86735099661713.2955870632302692.45067969662000.636202658
#Sta/Elev= 30
       0 2300.81    23.6 2282.11    37.4 2274.74    52.2 2260.48    66.9 2250.21
    71.7 2244.78    81.3 2240.41   129.4 2201.82   167.9 2176.31   201.6 2157.55
  258.132110.131     270 2108.66  315.242110.129   327.7 2113.75   371.7 2111.55
   394.2 2114.08     429 2113.27   456.9 2116.07   620.2 2118.94   640.3 2118.08
   659.8 2120.08   797.6 2123.51   873.7 2132.18   911.9 2138.54   942.8 2146.09
   964.7 2146.86     975 2150.99  1002.7  2154.9    1035 2164.07  1058.3  2168.3
#Mann= 7 ,-1,0
       0      .1       0  258.13    .045       0  315.24      .1       0
  509.36     .05       0  709.36      .1       0  849.36     .06       0
  969.36      .1       0
Bank Sta=258.13,315.24
XS Rating Curve= 0 ,0
Exp/Cntr=0.3,0.1

Type RM Length L Ch R = 1 ,4221    ,528.8,540.3,550
XS GIS Cut Line= 4
     2301500.971      661780.5982301795.91325174662029.048157336
2302107.30610886662158.0864010782302608.49706142662214.738376163
#Sta/Elev= 30
       0 2318.25    56.5 2284.04    77.4 2273.19   138.9 2235.06   168.5 2224.15
   208.2 2214.99   223.9 2209.17   252.5 2191.07   340.5  2141.2     366 2133.98
   396.4 2133.18   429.2 2105.87     438 2103.35   468.6  2106.8     490 2105.15
   524.5 2103.87  531.88 2105.11   572.1 2106.24   585.1 2104.73   670.6 2110.16
   767.9 2109.87   876.6 2116.72  1033.5 2129.69  1061.7 2129.93  1114.1 2135.89
  1134.2 2141.74  1146.3 2148.26  1198.6 2148.13  1214.7 2150.45  1227.1 2156.02
#Mann= 5 ,-1,0
       0      .1       0     490    .045       0  531.88      .1       0
 1032.71     .06       0 1227.09      .1       0
Bank Sta=490,531.88
XS Rating Curve= 0 ,0
Exp/Cntr=0.3,0.1

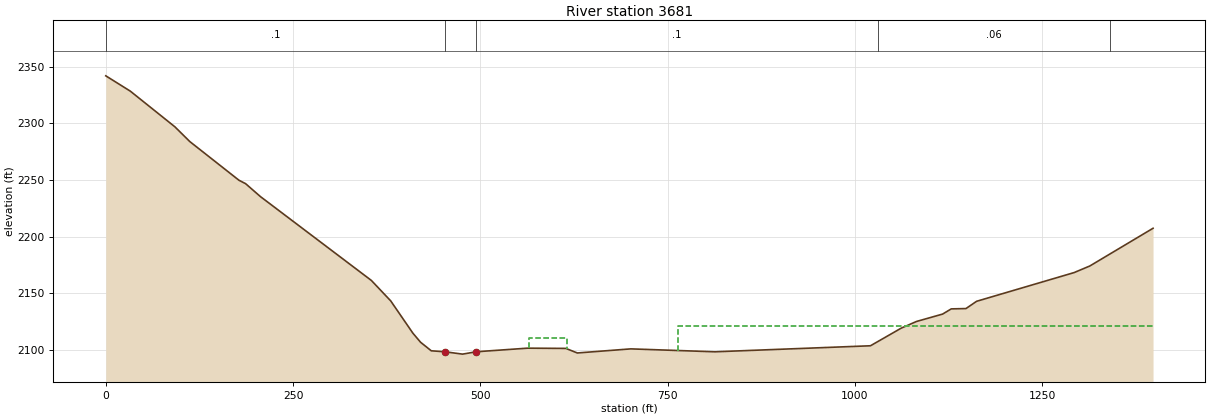
Type RM Length L Ch R = 1 ,3681    ,490,489,488.1
XS GIS Cut Line= 4
2301226.73852875661994.8333141652301470.82261686662326.553377099
2301836.82875708 662788.32489065   2302048.23398663124.658881851
#Sta/Elev= 30
       0 2342.01    32.7 2328.52    92.3 2297.01   112.2    2284   177.9 2249.84
   186.7 2246.85   206.5 2235.45   354.6 2161.47   380.4 2143.46   410.1  2114.9
   420.3 2106.93   434.6 2099.38   452.7 2098.53   476.4 2096.45  494.542098.532
   563.2 2101.71   614.3 2101.49   629.6 2097.47     701 2101.08   813.3  2098.5
    1021 2103.82  1062.1 2119.39  1082.4 2125.25  1117.3 2131.78  1128.9 2136.37
  1148.5 2136.65  1162.7 2143.06    1293 2168.42  1313.9 2174.23  1398.3  2207.5
#Mann= 5 ,-1,0
       0      .1       0   452.7    .045       0  494.54      .1       0
 1031.07     .06       0 1341.07      .1       0
#XS Ineff= 2 ,-1
  565.37  615.38 2110.68   763.9 1610.25 2121.65
Permanent Ineff=
       F       F
Bank Sta=452.7,494.54
XS Rating Curve= 0 ,0
Exp/Cntr=0.3,0.1