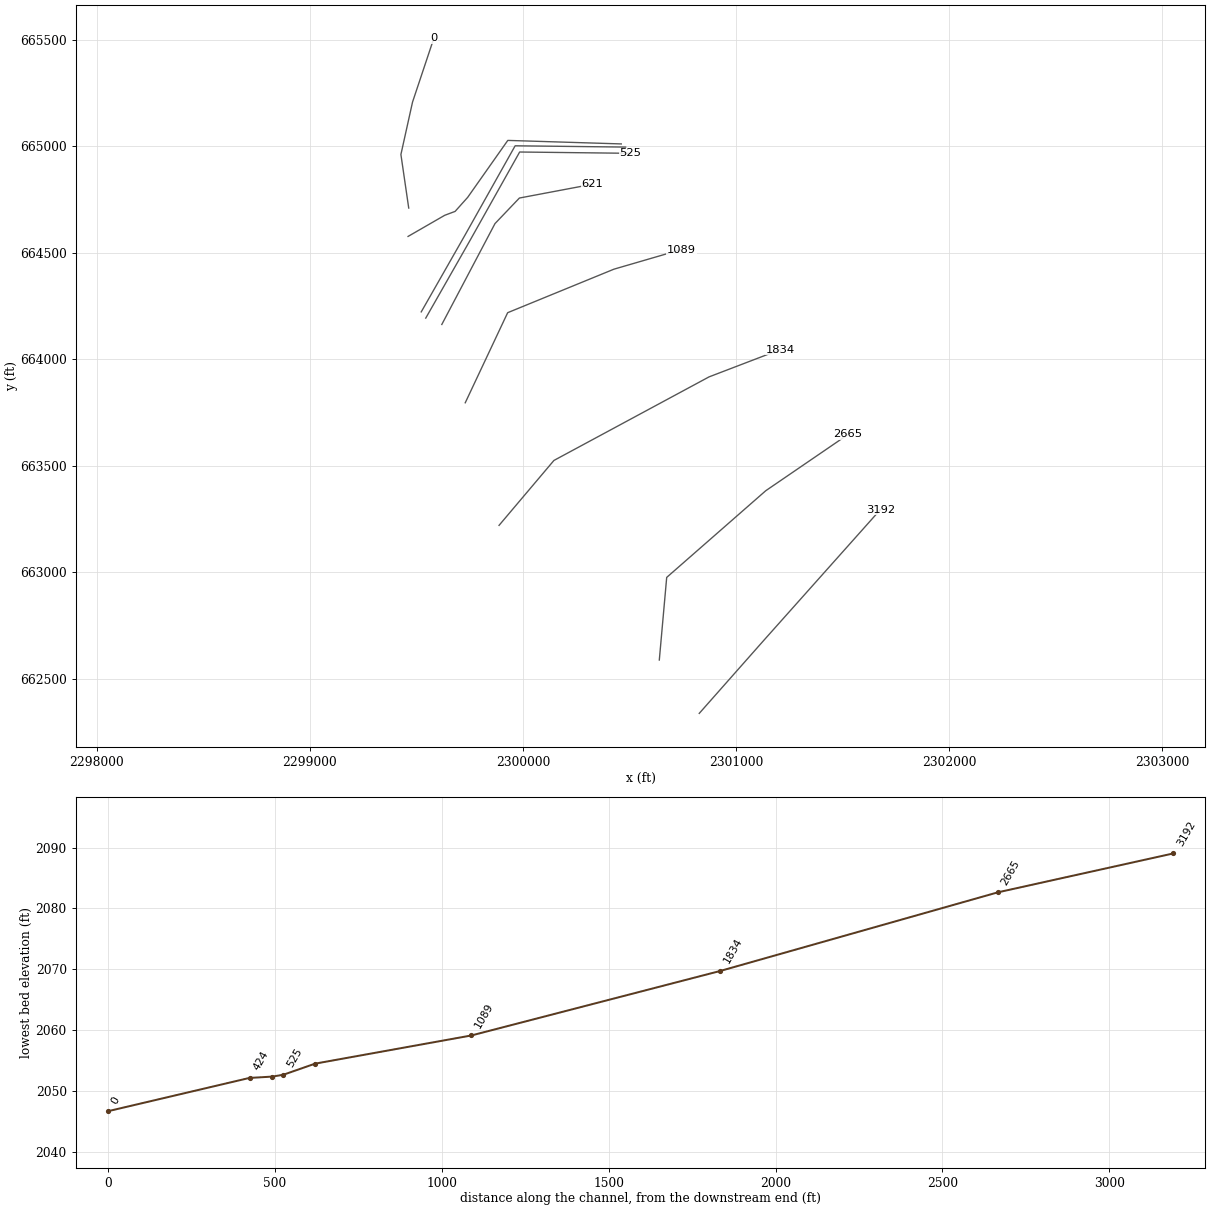
HEC-RAS study RFFILESCK.prj: RFFILESCK

--- RFFILESCK.g01 (geometry) --- (continued)

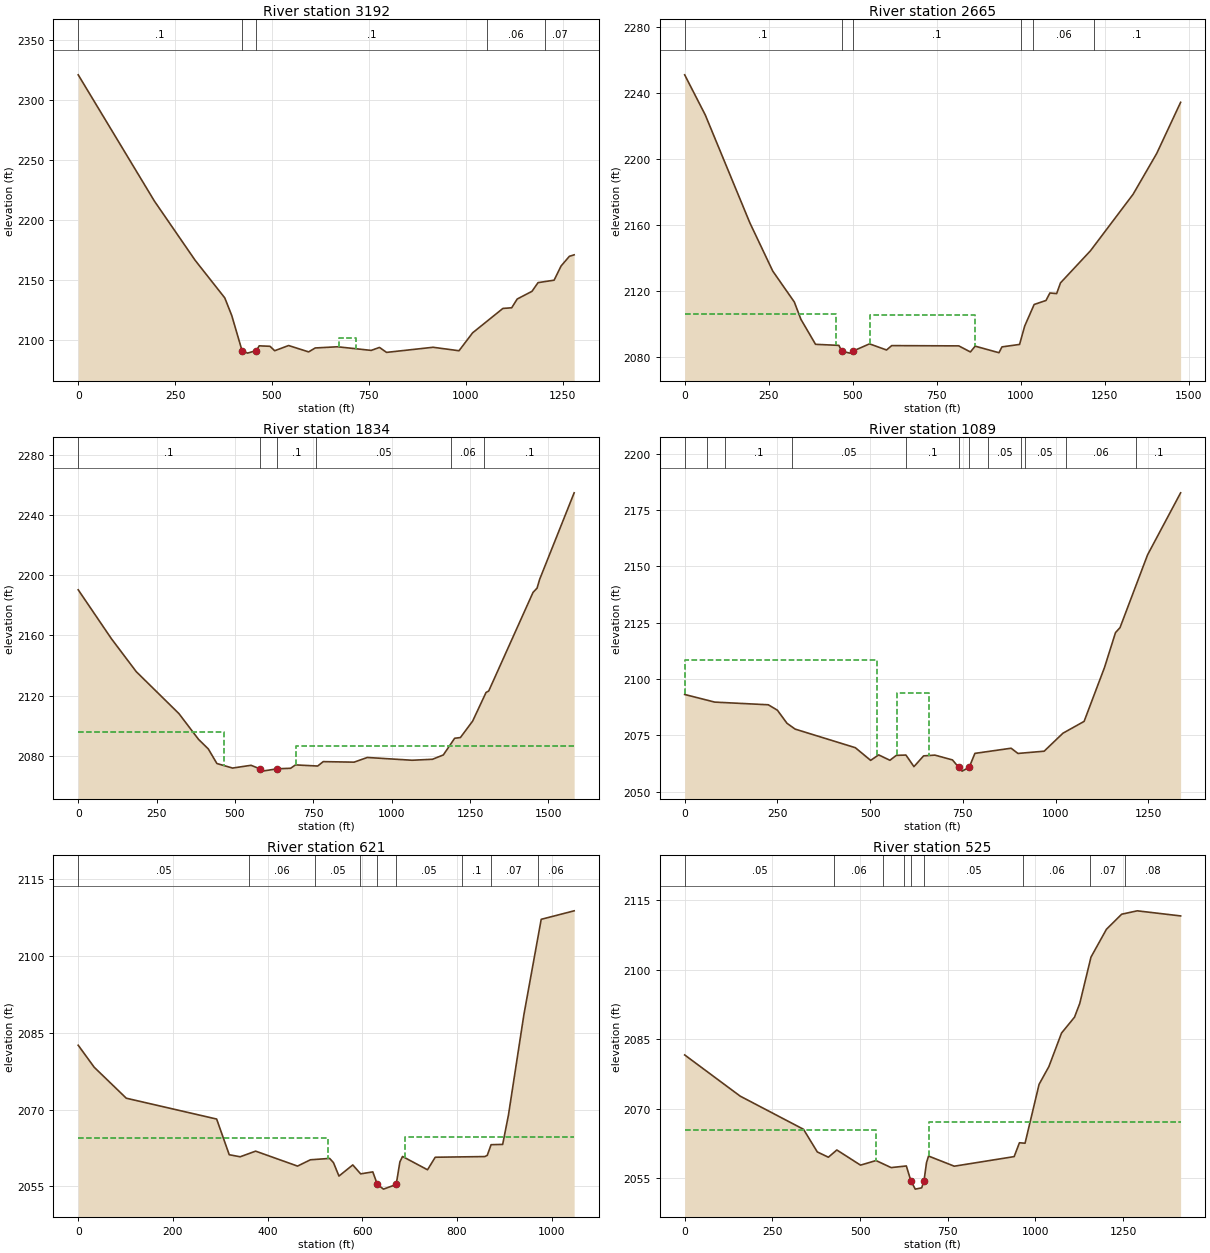
Type RM Length L Ch R = 1 ,3192    ,529.2,526.3,524.9
XS GIS Cut Line= 3
     2300828.162       662337.72     2301129.525      662678.609
2301678.60475584663294.401070506
#Sta/Elev= 30
       0 2321.08   196.8 2215.75     302 2166.36   378.3  2135.1   396.4  2120.3
   422.8 2091.16   437.1 2089.05  459.982091.229   467.2 2095.13     495 2094.75
   507.1 2091.05   543.1 2095.39   594.7 2090.08   611.7 2093.35   669.3 2094.35
   756.2 2091.33   777.5  2093.8   795.8 2089.67   915.8 2093.93   982.8 2091.04
  1017.9 2105.96  1096.1 2126.31  1118.8 2126.86    1133 2134.16  1171.2 2140.58
  1186.8 2147.82  1228.3 2149.87  1246.2 2161.67  1267.7 2169.78    1280    2171
#Mann= 5 ,-1,0
       0      .1       0   422.8    .045       0  459.98      .1       0
    1055     .06       0    1205     .07       0
#XS Ineff= 1 ,-1
  672.62  716.52 2101.34
Permanent Ineff=
       F
Bank Sta=422.8,459.98
XS Rating Curve= 0 ,0
Exp/Cntr=0.3,0.1

Type RM Length L Ch R = 1 ,2665    ,832.9,831.2,825.3
XS GIS Cut Line= 4
2300640.68197818662588.176587656 2300675.3713471662975.960126483
2301140.29152788663382.7866529622301526.90936242 663647.05707151
#Sta/Elev= 30
       0 2251.07    61.2 2226.82   193.8 2161.55     262 2132.31   326.3 2113.55
   345.7 2103.14   389.3 2087.97   458.8 2087.32  466.962083.854   491.4 2082.64
  500.542083.846   549.9 2088.25   600.5 2084.54   615.9 2087.19   815.6 2087.02
     850 2083.34   864.2 2086.86     935 2082.88   943.9 2086.42   996.3  2087.9
  1011.6 2099.06  1039.7 2112.08  1074.9 2114.51  1086.5 2119.04  1106.6 2118.68
  1118.1 2125.17  1207.3 2144.61    1334 2178.78  1404.3 2203.48  1475.4 2234.43
#Mann= 6 ,-1,0
       0      .1       0  466.96    .045       0  500.54      .1       0
  999.33     .07       0 1037.12     .06       0 1217.12      .1       0
#XS Ineff= 2 ,-1
       0  448.69 2106.61     550     865    2106
Permanent Ineff=
       F       F
Bank Sta=466.96,500.54
XS Rating Curve= 0 ,0
Exp/Cntr(USF)=0,0
Exp/Cntr=0.3,0.1

Type RM Length L Ch R = 1 ,1834    ,749.4,745.2,738.2
XS GIS Cut Line= 4
2299888.39329556663220.2024517492300146.01595077663524.964750646
2300874.10407067663917.1969454692301206.64840576 664044.53632889
#Sta/Elev= 30
       0 2190.31   105.6 2157.88     185 2135.91   321.3 2107.97   383.8 2090.85
   415.1 2084.46   442.4 2074.78   492.4 2071.75   551.4 2073.59  579.082071.266
   587.8 2069.71  635.172071.264   677.8 2071.61   693.1 2073.85     764  2073.1
   781.7 2076.03   880.2 2075.68   922.4 2078.79  1065.2 2076.95  1130.2 2077.59
  1164.8 2080.47    1201 2091.57  1219.3 2092.04  1258.3 2102.97  1301.1 2122.02
  1309.7 2123.04    1451 2188.57  1463.9 2191.45  1472.3 2197.36  1582.2 2254.81
#Mann= 6 ,-1,0
       0      .1       0  579.08    .045       0  635.17      .1       0
  759.06     .05       0 1189.06     .06       0 1296.08      .1       0
#XS Ineff= 2 , 0
          466.48 2095.71  693.76         2086.73
Permanent Ineff=
       F       F
Bank Sta=579.08,635.17
XS Rating Curve= 0 ,0
Exp/Cntr(USF)=0,0
Exp/Cntr=0.3,0.1

Type RM Length L Ch R = 1 ,1089    ,457.7,468.4,472.8
XS GIS Cut Line= 4
2299729.74617258663795.6755414442299928.81897159664218.498702249
2300427.72971769664422.803029551 2300744.6795278664515.036692253
#Sta/Elev= 30
       0 2093.14    81.1 2089.75   225.4 2088.56   249.9 2086.16   275.8 2080.33
   297.9 2077.75   459.9 2069.51   501.2 2063.88   522.8 2066.31   553.1 2063.92
   570.4 2066.09   596.3 2066.24   617.9  2061.1   643.9 2065.87   674.4 2066.21
   721.7 2064.08  738.272060.823   747.6  2059.1  766.86 2060.82   782.2 2066.98
   879.8 2069.27   898.2 2066.95   968.8 2067.95  1019.4 2075.93  1076.5 2081.19
  1131.4  2105.1  1161.1 2120.61  1173.3 2122.83  1247.5 2155.14  1336.6 2182.69
#Mann= 12 ,-1,0
       0      .1       0      60     .05       0     110      .1       0
     290     .05       0  597.34      .1       0  738.27    .045       0
  766.86      .1       0  817.34     .05       0  907.34     .06       0
  917.34     .05       0 1026.46     .06       0 1216.46      .1       0
#XS Ineff= 2 ,-1
       0  518.56 2108.64  573.14  658.05 2093.73
Permanent Ineff=
       F       F
Bank Sta=738.27,766.86
XS Rating Curve= 0 ,0
Exp/Cntr(USF)=0,0
Exp/Cntr=0.3,0.1

Type RM Length L Ch R = 1 ,621     ,87.8,95.2,97.8
XS GIS Cut Line= 4
 2299619.7582125664163.2911658232299869.35188194664636.769285535
2299983.97215074664756.7456416612300324.61930474664821.018689586
#Sta/Elev= 30
       0 2082.57    33.8 2078.27   101.6 2072.22   292.5 2068.15   319.1 2061.18
   342.2 2060.78   374.8 2061.88   463.4 2058.96   490.5 2060.19   531.2 2060.46
   539.3 2059.64   550.9 2057.01   580.1 2059.19   596.7 2057.44   622.4 2057.83
     632 2055.38     645 2054.46  671.84 2055.37   679.6 2059.77   685.2 2060.84
     738 2058.24   754.3 2060.69   859.2 2060.82   864.2 2061.06   872.3 2063.14
   896.8  2063.2     909 2068.93   941.5 2088.48   978.2 2107.17  1047.8 2108.83
#Mann= 9 ,-1,0
       0     .05       0     360     .06       0     500     .05       0
  595.24      .1       0     632    .045       0  671.84     .05       0
  811.16      .1       0  871.16     .07       0  971.16     .06       0
#XS Ineff= 2 , 0
           527.8 2064.45  690.26         2064.58
Permanent Ineff=
       F       F
Bank Sta=632,671.84
XS Rating Curve= 0 ,0
Exp/Cntr(USF)=0,0
Exp/Cntr=0.3,0.1

Type RM Length L Ch R = 1 ,525     ,32.9,32.8,32.7
XS GIS Cut Line= 4
2299544.40034776 664193.150609622299750.42691685 664554.66065303
 2299985.1844249664972.778552035 2300503.7199858664966.668794606
#Sta/Elev= 30
       0  2081.6   158.2 2072.71   338.8 2065.55   378.2 2060.66   409.8 2059.52
   433.9 2061.08   501.4 2057.81   545.6  2058.8   588.7 2057.28   632.1 2057.63
     645 2054.43   657.5 2052.63   675.9 2052.91  682.54 2054.47   689.6 2058.35
   695.4 2059.77   768.8 2057.58   939.5 2059.65   954.6 2062.64   970.6 2062.54
  1010.6 2075.26  1038.6 2079.09  1074.6 2086.32  1111.7 2089.76  1126.6 2092.72
  1158.6 2102.72  1202.6 2108.72  1246.1 2111.98  1290.6 2112.71  1414.2 2111.61
#Mann= 9 ,-1,0
       0     .05       0   426.1     .06       0   566.1     .05       0
   626.1      .1       0     645    .045       0  682.54     .05       0
  965.61     .06       0 1155.61     .07       0 1255.61     .08       0
#XS Ineff= 2 , 0
          546.73 2065.32  697.89         2067.17
Permanent Ineff=
       F       F
Bank Sta=645,682.54
XS Rating Curve= 0 ,0
Exp/Cntr(USF)=0,0
Exp/Cntr=0.3,0.1

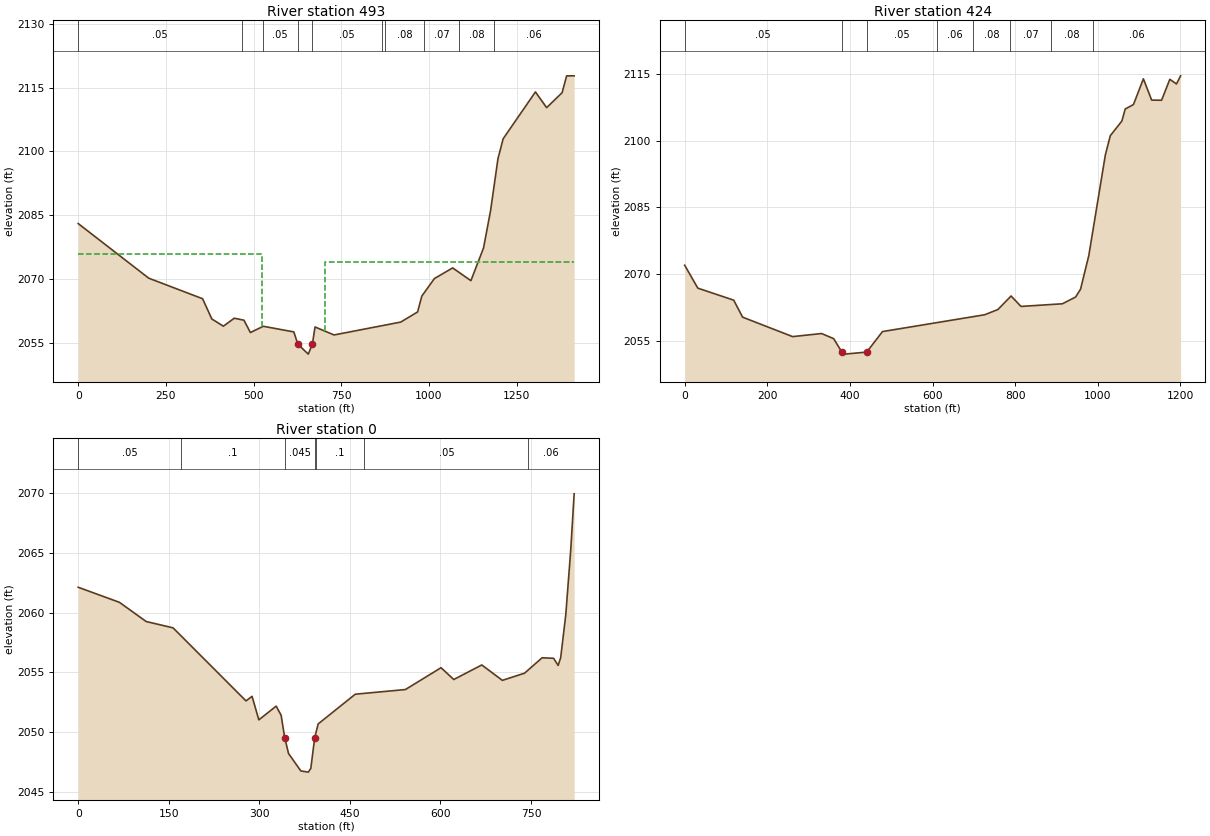
Type RM Length L Ch R = 1 ,493     ,72.6,68.5,66.1
XS GIS Cut Line= 4
2299523.25737848664222.3702344242299729.28394757664583.880277834
2299964.04145562 665001.998176842300482.57701652 664995.88841941
#Sta/Elev= 30
       0 2083.04   201.2 2070.19   354.7 2065.36     381  2060.6   413.9  2058.9
   445.1 2060.78   472.6 2060.31     491 2057.41   527.7 2058.88   614.8 2057.56
626.31282054.661   656.1 2052.33667.71652054.682   675.3 2058.72   729.5 2056.84
   919.7 2059.87   967.8 2062.25   979.9 2065.99  1015.8 2070.11  1067.8 2072.61
  1119.8 2069.61  1155.8  2077.3  1175.8 2086.04    1197 2098.33  1211.8 2102.99
  1303.8    2114  1335.8 2110.31  1379.8 2113.82  1392.8 2117.78  1414.2 2117.79
#Mann= 10 ,-1,0
       0     .05       0   466.1     .06       0   526.1     .05       0
626.3128    .045       0667.7165     .05       0   866.1     .06       0
   876.1     .08       0  985.61     .07       0 1085.61     .08       0
 1185.61     .06       0
#XS Ineff= 2 , 0
          524.48 2075.89  702.38         2074.02
Permanent Ineff=
       F       F
Bank Sta=626.3128,667.7165
XS Rating Curve= 0 ,0
Exp/Cntr(USF)=0,0
Exp/Cntr=0.3,0.1

Type RM Length L Ch R = 1 ,424     ,413.9,424.2,432.2
XS GIS Cut Line= 6
2299461.33892003664576.5372760352299633.60140064664675.806998554
2299682.19182487664694.0284076412299741.19448287664759.972554812
2299929.48237676665027.2198880822300462.24167101665010.733851289
#Sta/Elev= 30
       0 2072.05    31.8 2066.91   118.7 2064.21   140.2  2060.4   261.2 2056.04
   331.3 2056.73   360.6 2055.58   380.3 2052.59   387.2 2052.11  440.55 2052.57
   478.8 2057.17     726 2060.94     758 2062.11     790 2065.15     814 2062.81
   914.1  2063.4   946.1 2064.91   958.1 2066.67   978.1 2074.23  1018.1 2096.76
  1030.1  2101.1  1058.2  2104.4  1066.2 2107.09  1086.2 2108.09  1110.2 2113.86
  1130.2 2109.09  1154.2 2109.05  1174.2 2113.75  1190.2 2112.71  1200.3 2114.53
#Mann= 8 ,-1,0
       0     .05       0   380.3    .045       0  440.55     .05       0
  610.37     .06       0  697.28     .08       0  787.28     .07       0
  887.28     .08       0  987.28     .06       0
Bank Sta=380.3,440.55
XS Rating Curve= 0 ,0
Exp/Cntr(USF)=0,0
Exp/Cntr=0.3,0.1

Type RM Length L Ch R = 1 ,0       ,,,
XS GIS Cut Line= 4
2299464.43829591664709.7186380242299427.75576398664961.101088313
2299482.21702256665206.7545874812299582.20352972665506.364958155
#Sta/Elev= 30
       0 2062.12    68.2 2060.86   112.6 2059.25   157.1 2058.72   277.9  2052.6
     288 2052.98   299.2 2051.01   327.9 2052.16   336.1  2051.4  342.022049.529
   348.4 2048.19   368.8 2046.73   381.1 2046.63   385.3 2046.94  391.782049.528
   397.5 2050.67     459 2053.16     542 2053.55     601 2055.38   622.1 2054.39
   668.5 2055.61   702.6 2054.32   739.3 2054.92   768.4 2056.21   787.4 2056.17
     795 2055.57   799.2 2056.22   807.6  2059.8   815.8 2065.21   821.5 2069.95
#Mann= 7 ,-1,0
       0     .05       0     170      .1       0  342.02    .045       0
  391.78     .05       0  394.04      .1       0  474.04     .05       0
  745.66     .06       0
Bank Sta=342.02,391.78
XS Rating Curve= 0 ,0
Exp/Cntr=0.3,0.1
LCMann Table=0

Chan Stop Cuts=-1
Use User Specified Reach Order=0
Composite Channel Slope=5